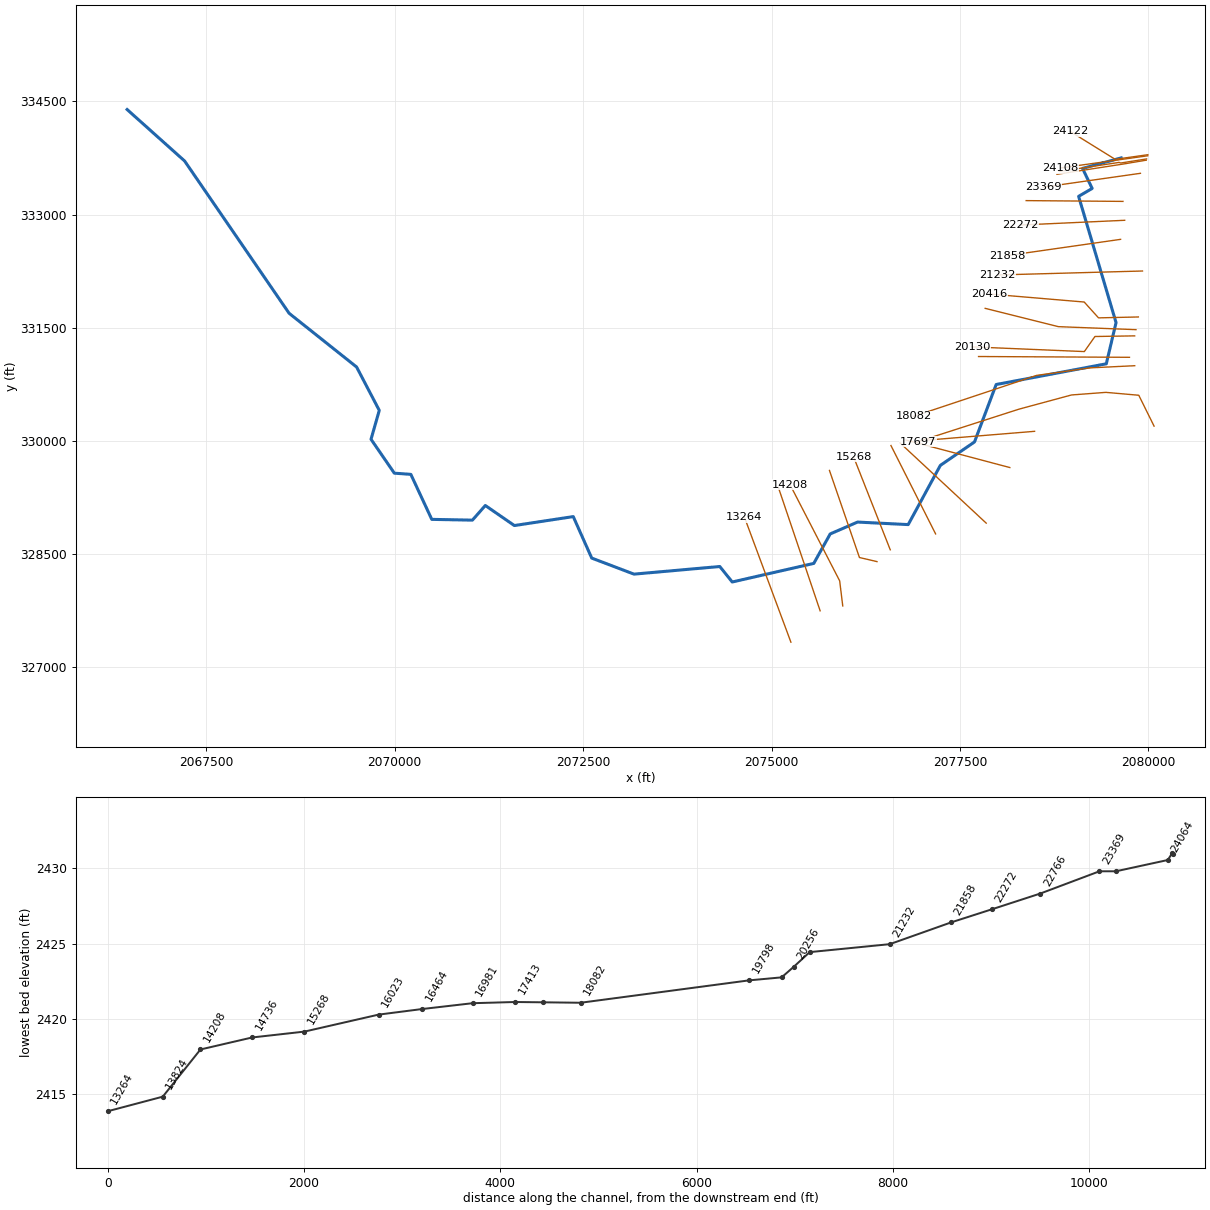
--- OTTERCK.prj (project) ---

Proj Title=OTTERCK
Current Plan=p01
Default Exp/Contr=0,0
English Units
Geom File=g01
Flow File=f01
Plan File=p01
BEGIN DESCRIPTION:
Stream Name- Otter Creek
Flood Zone: Zone A
Greenbrier County, WV
County-Wide Study
WVDHSEM-2018-3, Flood Risk Project
HEC-RAS Version: 5.0.7
General Notes:
For the Hydrology regression was used.
END DESCRIPTION:
DSS Export Rating Curves= 0
DSS Export Rating Curve Sorted= 0
DSS Export Volume Flow Curves= 0
DXF OffsetX= 0
DXF OffsetY= 0
DXF ScaleX= 0
DXF ScaleY= 0

--- OTTERCK.p01 (plan) ---

Plan Title=Floodplain
Program Version=5.07
Short Identifier=Floodplain
Geom File=g01
Flow File=f01
Subcritical Flow
K Sum by GR= 0
Std Step Tol= 0.01
Critical Tol= 0.01
Num of Std Step Trials= 20
Max Error Tol= 0.3
Flow Tol Ratio= 0.001
Split Flow NTrial= 30
Split Flow Tol= 0.02
Split Flow Ratio= 0.02
Log Output Level= 0
Friction Slope Method= 1
Unsteady Friction Slope Method= 2
Unsteady Bridges Friction Slope Method= 1
Parabolic Critical Depth
Global Vel Dist= 0 , 0 , 0
Global Log Level= 0
CheckData=True
Encroach Param=-1 ,0,0, 0
Mapping Interval=1HOUR
Computation Time Step Use Courant=        0
Computation Time Step Use Time Series=    0
Computation Time Step Count To Double=0
Computation Time Step Max Doubling=0
Computation Time Step Max Halving=0
Computation Time Step Residence Courant=0
Run HTab= 0
Run UNet= 0
Run Sediment= 0
Run PostProcess= 0
Run WQNet= 0
Run RASMapper=-1
UNET Theta= 0
UNET Theta Warmup= 0
UNET ZTol= 0
UNET ZSATol= 0
UNET MxIter= 0
UNET Max Iter WO Improvement= 0
UNET MaxInSteps= 0
UNET DtIC= 0
UNET DtMin= 0
UNET MaxCRTS= 0
UNET WFStab= 0
UNET SFStab= 0
UNET WFX= 1
UNET SFX= 1
UNET 1D Methodology=Finite Difference
UNET DSS MLevel= 1
UNET Pardiso=0
UNET DZMax Abort= 0
UNET Use Existing IB Tables= 0
UNET Froude Reduction=False
UNET Froude Limit= 0
UNET Froude Power= 0
UNET D1 Cores= 0
UNET D2 Coriolis=0
UNET D2 Cores= 0
UNET D2 Theta= 1
UNET D2 Theta Warmup= 1
UNET D2 Z Tol= 0.01
UNET D2 Volume Tol= 0.01
UNET D2 Max Iterations= 20
UNET D2 Equation= 0
UNET D2 RampUpFraction=0.1
UNET D2 TimeSlices= 1
UNET D2 BCVolumeCheck=0
UNET D1D2 MaxIter= 0
UNET D1D2 ZTol=0.01
UNET D1D2 QTol=0.1
UNET D1D2 MinQTol=1
Write IC File= 0
Write IC File at Fixed DateTime=0
Write IC File at Sim End=0
Echo Input=False
Echo Parameters=False
Echo Output=False
Write Detailed= 0
HDF Write Warmup=0
HDF Write Time Slices=0
HDF Flush=0
HDF Face Node Velocities=0
HDF Compression= 1
HDF Chunk Size= 1
HDF Spatial Parts= 1
HDF Use Max Rows=0
HDF Fixed Rows= 1
Calibration Method= 0
Calibration Iterations= 20
Calibration Max Change=0.05
Calibration Tolerance=0.2
Calibration Maximum=1.5
Calibration Minimum=0.5
Calibration Optimization Method= 1
WQ AD Non Conservative
WQ ULTIMATE=-1
WQ Max Comp Step=1HOUR
WQ Output Interval=15MIN
WQ Output Selected Increments= 0
WQ Output face flow=0
WQ Output face velocity=0
WQ Output face area=0
WQ Output face dispersion=0
WQ Output cell volume=0
WQ Output cell surface area=0
WQ Output cell continuity=0
WQ Output cumulative cell continuity=0
WQ Output face conc=0
WQ Output face dconc_dx=0
WQ Output face courant=0
WQ Output face peclet=0
WQ Output face adv mass=0
WQ Output face disp mass=0
WQ Output cell mass=0
WQ Output cell source sink temp=0
WQ Output nsm pathways=0
WQ Output nsm derived pathways=0
WQ Output MaxMinRange=-1
WQ Daily Max Min Mean=-1
WQ Daily Range=0
WQ Daily Time=0
WQ Create Restart=0
WQ Fixed Restart=0
WQ System Summary=0
WQ Write To DSS=0
WQ Use Fixed Temperature=0
Sorting and Armoring Iterations= 10
XS Update Threshold= 0.02
Bed Roughness Predictor= 0
Hydraulics Update Threshold= 0.02
Energy Slope Method= 1
Volume Change Method= 1
Sediment Retention Method= 0
XS Weighting Method= 0
Number of US Weighted Cross Sections= 1
Number of DS Weighted Cross Sections= 1
Upstream XS Weight=0
Main XS Weight=1
Downstream XS Weight=0
Number of DS XS's Weighted with US Boundary= 1
Upstream Boundary Weight= 1
Weight of XSs Associated with US Boundary= 0
Number of US XS's Weighted with DS Boundary= 1
Downstream Boundary Weight= 0.5
Weight of XSs Associated with DS Boundary= 0.5
Percentile Method= 0
Sediment Output Level= 3
Mass or Volume Output= 0
Output Increment Type= 1
Profile and TS Output Increment= 1
XS Output Flag= 0
XS Output Increment= 10
Write Gradation File= 0
Read Gradation Hotstart= 0
Write HDF5 File= 1
Write Binary Output= 1
Write DSS Sediment File= 0
SV Curve= 0
Specific Gage Flag= 0

--- OTTERCK.f01 (steady flow) ---

Flow Title=Flow
Program Version=5.07
Number of Profiles= 6
Profile Names=f1p,f10p,f4p,f2p,f02p,f1pplus
River Rch & RM=OTTERCK,Main            ,24122
     543     286     381     459     759     803
River Rch & RM=OTTERCK,Main            ,18082
     748     399     528     635    1040    1110
River Rch & RM=OTTERCK,Main            ,17413
    1230     669     877    1050    1690    1820
River Rch & RM=OTTERCK,Main            ,10863
    1660     913    1190    1420    2270    2450
River Rch & RM=OTTERCK,Main            ,7423
    1980    1100    1420    1690    2700    2920
River Rch & RM=OTTERCK,Main            ,6332
    2200    1230    1590    1890    3000    3250
River Rch & RM=OTTERCK,Main            ,128
    2710    1520    1960    2320    3680    4010
Boundary for River Rch & Prof#=OTTERCK,Main            , 1
Up Type= 0
Dn Type= 1
Dn Known WS=2408.71
Boundary for River Rch & Prof#=OTTERCK,Main            , 2
Up Type= 0
Dn Type= 1
Dn Known WS=2407.47
Boundary for River Rch & Prof#=OTTERCK,Main            , 3
Up Type= 0
Dn Type= 1
Dn Known WS=2407.97
Boundary for River Rch & Prof#=OTTERCK,Main            , 4
Up Type= 0
Dn Type= 1
Dn Known WS=2408.34
Boundary for River Rch & Prof#=OTTERCK,Main            , 5
Up Type= 0
Dn Type= 1
Dn Known WS=2409.18
Boundary for River Rch & Prof#=OTTERCK,Main            , 6
Up Type= 0
Dn Type= 1
Dn Known WS=2409.41
DSS Import GetInterval= 0
DSS Import GetPeak= 0
DSS Import FillOption= 0

--- OTTERCK.g01 (geometry) ---

Geom Title=Geometry
Program Version=5.07

River Reach=OTTERCK         ,Main
Reach XY= 30
2079637.82699999333751.0200000112079126.14869511333611.886943713
2079253.51200002333345.6860000042079073.69400001333241.274000004
2079570.35600004331566.7800000012079441.01899999331019.893000007
     2077979.891330745.0690000062077692.72100002      329983.309
     2077239.521329672.2169999932076813.29200003328886.944000021
2076141.20900002328920.4370000212075778.37300003      328763.022
2075560.67199999328372.2759999932074478.86300004328125.547999993
     2074313.634328330.9689999972073175.43500003328229.758000001
2072614.94100001328442.7440000182072369.95100003328993.004000008
2071588.80399999328874.3079999982071203.29500002329140.371000022
2071032.48400003328946.1139999932070493.25400001328956.162000015
2070215.26600003329553.445000008     2069996.449329569.075000018
2069687.20100001330018.9909999972069796.70300004330402.100000009
2069495.78800002330977.5250000062068600.76100004331689.850999996
2067214.43600002333710.2610000222066451.98403847334392.799541429

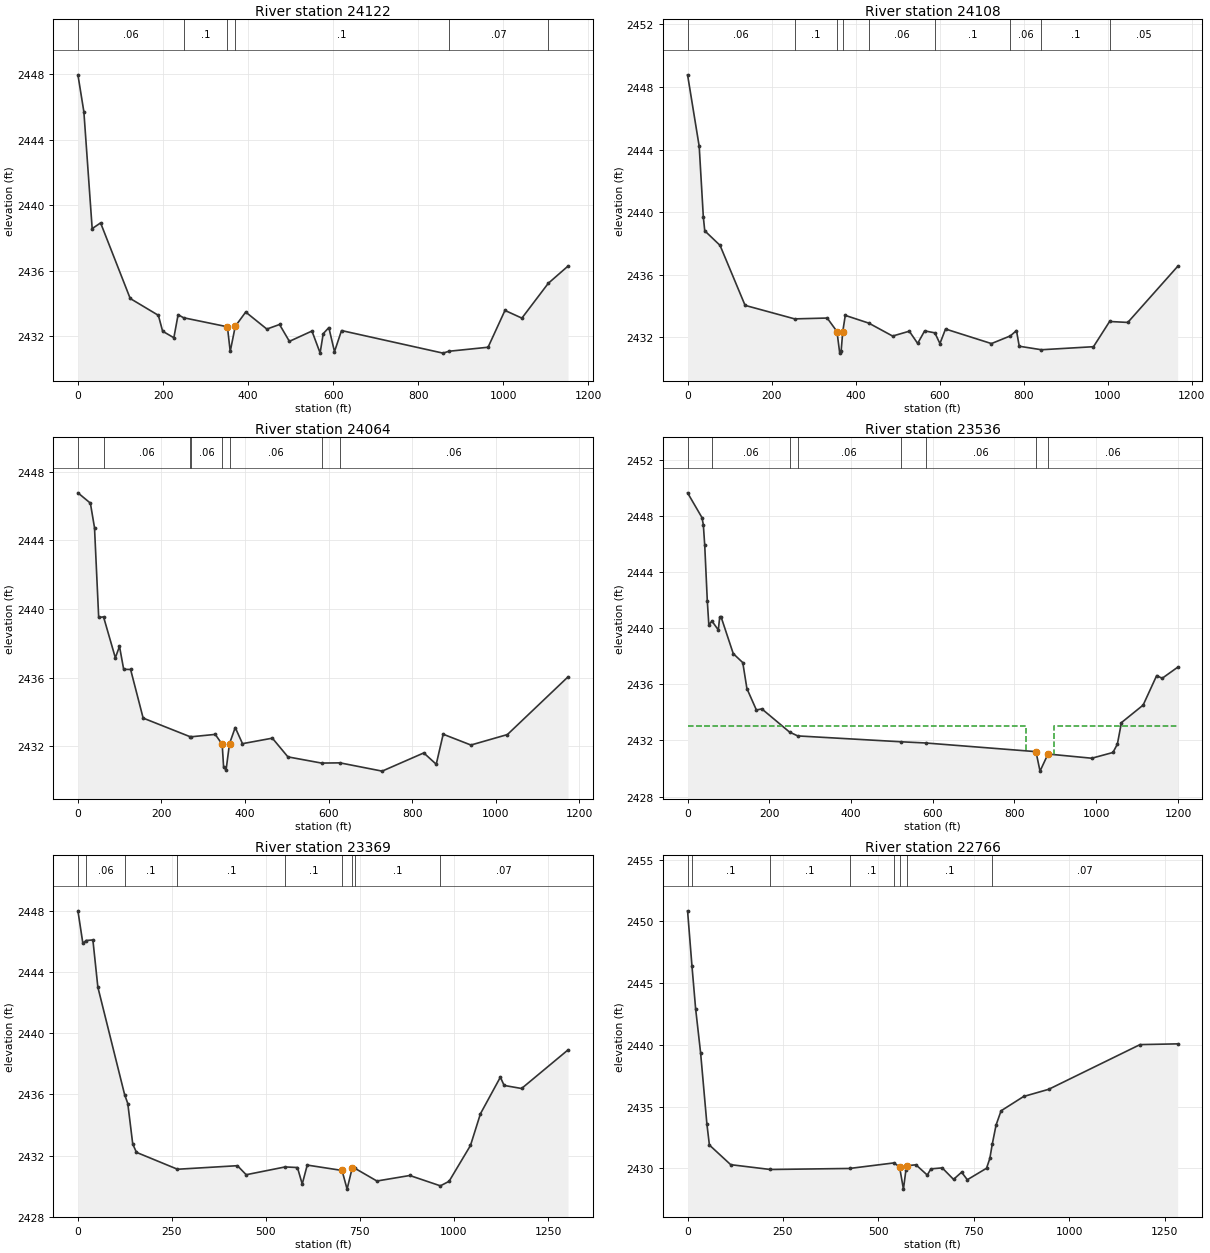
Type RM Length L Ch R = 1 ,24122   ,14.2,14.2,14.2
XS GIS Cut Line= 3
2079992.50400634333793.5454785442079558.38588229333732.483714201
 2078956.4935266334105.873231036
#Sta/Elev= 30
       0 2447.98      14 2445.72    33.5 2438.58    53.3 2438.93   122.9 2434.31
   189.1 2433.28   199.1 2432.31   225.5 2431.91   235.5 2433.32  248.252433.133
   351.4 2432.58     358 2431.07  369.85 2432.61   394.4 2433.48   444.1 2432.44
   473.9 2432.72   497.1 2431.69   550.1 2432.32   569.3 2430.98   576.6 2432.16
   589.8 2432.53   603.1 2431.06   619.6 2432.35   858.1 2430.97  872.082431.084
   964.1 2431.33  1003.8 2433.58  1043.6 2433.11 1105.622435.2381152.011 2436.29
#Mann= 6 ,-1 , 0
       0     .06       0  248.25      .1       0   351.4    .045       0
  369.85      .1       0  872.08     .07       0 1105.62     .05       0
Bank Sta=351.4,369.85
XS Rating Curve= 0 ,0
Exp/Cntr(USF)=0,0
Exp/Cntr=0.5,0.3

Type RM Length L Ch R = 1 ,24108   ,47.2,43.9,549
XS GIS Cut Line= 2
2079989.96540425333779.3845716242078834.63348905333617.727089266
#Sta/Elev= 30
       0 2448.77    27.7  2444.2    37.5  2439.7    40.9 2438.81    77.3 2437.88
   136.9 2434.05  254.862433.187   332.4 2433.24   355.6 2432.38   362.2    2431
   365.5 2431.12  369.42 2432.38   375.4 2433.41  431.472432.915   488.1 2432.09
   527.8  2432.4   547.7 2431.62   564.3 2432.42  588.682432.295   600.7 2431.61
     614 2432.54   723.3 2431.61  768.32  2432.1   782.9 2432.44   789.5 2431.44
  842.292431.216   966.2 2431.41 1004.57 2433.02  1047.9 2432.96  1166.6 2436.54
#Mann= 9 ,-1 , 0
       0     .06       0  254.86      .1       0   355.6    .045       0
  369.42      .1       0  431.47     .06       0  588.68      .1       0
  768.32     .06       0  842.29      .1       0 1004.57     .05       0
Bank Sta=355.6,369.42
XS Rating Curve= 0 ,0
Exp/Cntr(USF)=0,0
Exp/Cntr=0.5,0.3

Type RM Length L Ch R = 1 ,24064   ,515.6,528.1,34.7
XS GIS Cut Line= 4
2079975.62371632 333737.767128912079632.14651067333683.456630581
2079611.59659238333691.5298127652078817.48903574333571.166005659
#Sta/Elev= 30
       0 2446.77    29.8 2446.17    39.7 2444.74    49.7 2439.51   61.342439.545
    89.6 2437.16    99.5 2437.83   109.5 2436.49   126.1 2436.48   156.1 2433.65
  269.182432.558  270.462432.559   328.7  2432.7   345.3 2432.12   348.7 2430.79
   354.6 2430.63   362.8 2432.16   376.5  2433.1   393.9 2432.16   465.4 2432.48
   502.6 2431.39  583.072431.029  627.232431.042   728.1 2430.56   827.8 2431.62
   857.6 2430.96   874.2 2432.71   940.6 2432.08  1027.9 2432.69    1173 2436.05
#Mann= 8 ,-1 , 0
       0    .055       0   61.34     .06       0  269.18      .1       0
  270.46     .06       0   345.3    .045       0   362.8     .06       0
  583.07      .1       0  627.23     .06       0
Bank Sta=345.3,362.8
XS Rating Curve= 0 ,0
Exp/Cntr(USF)=0,0
Exp/Cntr=0.5,0.3

Type RM Length L Ch R = 1 ,23536   ,164.5,167.7,163.3
XS GIS Cut Line= 3
2079971.22159138333720.9669756682079669.03394855 333670.43031652
2078786.59172834333533.985469025
#Sta/Elev= 30
       0 2449.66    35.3 2447.89    38.6 2447.38      42 2445.91    48.3 2441.95
      52 2440.25   59.772440.509    75.2 2439.88    78.6 2440.78    81.9 2440.82
   111.8 2438.19   135.1 2437.55   145.2  2435.7   168.4 2434.17   181.7 2434.25
  249.592432.595  269.522432.322  521.812431.904  583.012431.817   852.5  2431.2
   862.5 2429.81     882 2431.03   989.1 2430.73  1040.9 2431.14  1051.7 2431.73
  1061.7 2433.27  1114.8 2434.52    1148 2436.63  1161.3 2436.43  1199.3 2437.22
#Mann= 8 ,-1 , 0
       0    .055       0   59.77     .06       0  249.59      .1       0
  269.52     .06       0  521.81     .05       0  583.01     .06       0
   852.5    .045       0     882     .06       0
#XS Ineff= 2 , 0
          827.16    2433  897.12            2433
Permanent Ineff=
       F       F
Bank Sta=852.5,882
XS Rating Curve= 0 ,0
Exp/Cntr(USF)=0,0
Exp/Cntr=0.3,0.1

Type RM Length L Ch R = 1 ,23369   ,593.2,602.4,583.4
XS GIS Cut Line= 2
2079893.72292927333546.8836887842078603.42926273333362.979763899
#Sta/Elev= 30
       0 2447.98    13.2 2445.85   21.592446.042    39.8 2446.08      53    2443
  124.152435.983   132.6  2435.4   145.8 2432.75   155.7 2432.21  264.792431.108
   424.2 2431.34   447.4 2430.75  551.052431.259   583.8 2431.22   596.5 2430.14
   609.8 2431.38   702.3 2431.03   715.8 2429.81   729.4 2431.19  736.752431.167
   795.1 2430.34   882.6  2430.7  963.872430.025     987 2430.32  1043.9 2432.66
  1070.4 2434.73  1123.4 2437.12  1133.4 2436.58  1179.8 2436.38  1303.3  2438.9
#Mann= 9 ,-1 , 0
       0      .1       0   21.59     .06       0  124.15      .1       0
  264.79      .1       0  551.05      .1       0   702.3    .045       0
   729.4      .1       0  736.75      .1       0  963.87     .07       0
Bank Sta=702.3,729.4
XS Rating Curve= 0 ,0
Exp/Cntr(USF)=0,0
Exp/Cntr=0.3,0.1

Type RM Length L Ch R = 1 ,22766   ,479.4,494.1,488.7
XS GIS Cut Line= 2
2079662.20115103333174.2813349062078377.83986917333184.663008085
#Sta/Elev= 30
       0 2450.86    11.62446.364    21.1 2442.94    34.2 2439.35    50.6 2433.62
    57.2  2431.9     113 2430.31  216.942429.919  424.482430.003  540.762430.452
   555.6 2430.13   565.7 2428.33   572.3 2429.89     576 2430.23   598.5  2430.3
   628.1 2429.47   637.9 2429.97   667.4 2430.05     697 2429.12   718.2  2429.7
   733.1 2429.09   783.5 2430.02   792.1 2430.81  798.492431.964   808.5 2433.52
   821.6 2434.67   880.7 2435.83   946.3 2436.41  1185.8 2440.03  1284.4 2440.09
#Mann= 8 ,-1 , 0
       0     .06       0    11.6      .1       0  216.94      .1       0
  424.48      .1       0  540.76      .1       0   555.6    .045       0
     576      .1       0  798.49     .07       0
Bank Sta=555.6,576
XS Rating Curve= 0 ,0
Exp/Cntr(USF)=0,0
Exp/Cntr=0.3,0.1

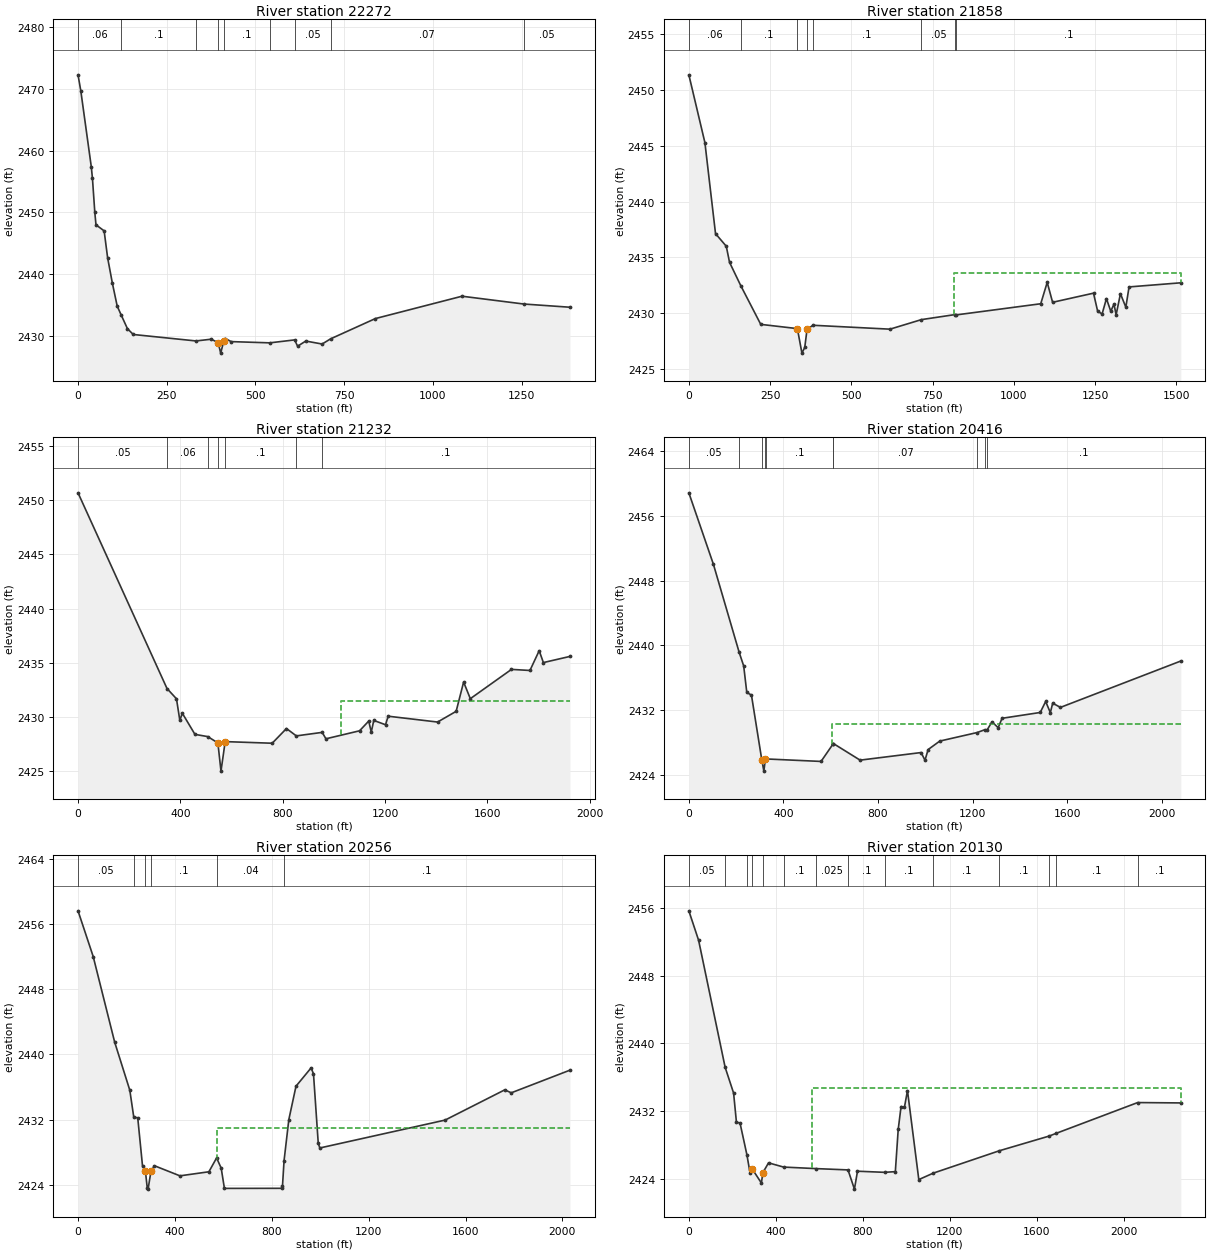
Type RM Length L Ch R = 1 ,22272   ,399.1,414.2,410.5
XS GIS Cut Line= 2
2079685.06829739332923.6291000982078300.48867929332860.447300097
#Sta/Elev= 30
       0 2472.22     7.9 2469.62    37.4 2457.37    40.7 2455.48    47.3 2450.02
    50.6    2448    73.6 2447.02    83.4 2442.68    96.7  2438.6   110.4 2434.87
  121.372433.471   139.2 2431.23   155.7 2430.29   332.42429.247   375.7 2429.53
   394.8 2428.96     402 2427.28   410.5 2429.19   415.1 2429.64   431.5 2429.14
  540.23 2428.94  610.142429.414   618.7  2428.4   641.7 2429.23   687.7 2428.75
  711.632429.587   837.7 2432.86  1081.8 2436.47 1255.85 2435.21    1386 2434.69
#Mann= 9 ,-1 , 0
       0     .06       0  121.37      .1       0   332.4      .1       0
   394.8    .045       0   410.5      .1       0  540.23      .1       0
  610.14     .05       0  711.63     .07       0 1255.85     .05       0
Bank Sta=394.8,410.5
XS Rating Curve= 0 ,0
Exp/Cntr(USF)=0,0
Exp/Cntr=0.3,0.1

Type RM Length L Ch R = 1 ,21858   ,584.6,625.7,605.2
XS GIS Cut Line= 2
2079630.50500799332670.8707359332078131.70925169332456.048305454
#Sta/Elev= 30
       0 2451.38    49.4  2445.3    82.1 2437.13   115.2    2436   125.2 2434.56
  159.682432.469   221.3 2428.99     334 2428.61     348 2426.41   356.7 2426.92
   363.8 2428.54  381.97 2428.91     619 2428.56   715.82429.417  819.882429.871
  822.452429.837    1083 2430.84  1102.9 2432.76  1119.5 2430.97  1245.4 2431.79
  1258.2 2430.16  1271.9 2429.93  1285.2  2431.3  1298.5 2430.17  1308.4 2430.81
    1315 2429.85  1328.3 2431.74  1344.9 2430.53  1354.8 2432.35  1514.1 2432.72
#Mann= 8 ,-1 , 0
       0     .06       0  159.68      .1       0     334    .045       0
   363.8      .1       0  381.97      .1       0   715.8     .05       0
  819.88     .07       0  822.45      .1       0
#XS Ineff= 2 , 0
                           817.1         2433.64
Permanent Ineff=
       F       F
Bank Sta=334,363.8
XS Rating Curve= 0 ,0
Exp/Cntr(USF)=0,0
Exp/Cntr=0.3,0.1

Type RM Length L Ch R = 1 ,21232   ,789.9,816.1,803.7
XS GIS Cut Line= 2
2079920.89358499332250.869318376 2077998.4064762332198.155962167
#Sta/Elev= 30
       0  2450.7  347.88  2432.6   384.9 2431.65     398 2429.66   407.9 2430.31
   457.1 2428.36  506.942428.154   546.8 2427.57   558.9 2424.96   575.3 2427.69
   759.1 2427.54   814.9  2428.9  853.462428.219  954.582428.545   969.1 2427.95
  1100.6 2428.69  1136.5 2429.59  1146.4 2428.57  1156.2 2429.65  1202.2 2429.25
  1212.4 2430.04  1405.6  2429.5  1478.2 2430.49  1507.4  2433.2  1533.6 2431.66
  1694.5 2434.37  1766.7 2434.27  1802.8  2436.1  1819.2    2435  1923.2 2435.57
#Mann= 7 ,-1 , 0
       0     .05       0  347.88     .06       0  506.94      .1       0
   546.8    .045       0   575.3      .1       0  853.46      .1       0
  954.58      .1       0
#XS Ineff= 2 , 0
                          1027.4         2431.45
Permanent Ineff=
       F       F
Bank Sta=546.8,575.3
XS Rating Curve= 0 ,0
Exp/Cntr(USF)=0,0
Exp/Cntr=0.3,0.1

Type RM Length L Ch R = 1 ,20416   ,157.4,159.6,157.8
XS GIS Cut Line= 4
2079866.34324598331641.1967839592079337.72612908331629.336784541
2079147.96613839331839.428202796 2077884.0290576331946.168197555
#Sta/Elev= 30
       0 2458.88   103.9 2450.03  212.642439.145   231.9 2437.45     245 2434.17
   264.7 2433.84   308.4 2425.83   317.2 2424.43   323.7 2425.94  325.03 2425.94
     559 2425.63  611.142427.847  611.562427.837   724.1 2425.79     982 2426.73
   998.5 2425.78  1011.8  2427.1  1061.1 2428.15 1219.222429.208 1252.472429.567
 1259.992429.468  1281.7 2430.53    1308 2429.81  1324.4 2430.97  1485.8 2431.69
  1508.8 2433.05  1528.6 2431.67  1538.5 2432.84  1571.4 2432.32  2080.3 2438.06
#Mann= 10 ,-1 , 0
       0     .05       0  212.64     .06       0   308.4    .045       0
   323.7     .06       0  325.03      .1       0  611.14    .025       0
  611.56     .07       0 1219.22      .1       0 1252.47     .07       0
 1259.99      .1       0
#XS Ineff= 2 , 0
                          607.01          2430.3
Permanent Ineff=
       F       F
Bank Sta=308.4,323.7
XS Rating Curve= 0 ,0
Exp/Cntr(USF)=0,0
Exp/Cntr=0.3,0.1

Type RM Length L Ch R = 1 ,20256   ,106,126.4,133.6
XS GIS Cut Line= 3
2079835.03437403331472.7947919062078805.78178157331512.660209219
2077834.51525067331755.476841946
#Sta/Elev= 30
       0 2457.62    62.7 2452.01   151.4  2441.5   213.8 2435.61   230.2  2432.3
   246.6 2432.22   266.3 2426.32   278.32425.673     286 2423.56   289.3 2423.47
  301.16 2425.65   315.6 2426.34   420.8  2425.1   540.4  2425.6   572.2  2427.3
   591.1 2426.05   604.5 2423.56   840.9 2423.57   844.2 2423.84   850.7 2426.96
   870.4    2432     900  2436.1   962.4 2438.35   972.2 2437.62   991.9 2429.08
   998.5 2428.52  1515.4 2431.94  1761.8 2435.65  1788.9 2435.29  2031.2 2438.07
#Mann= 6 ,-1 , 0
       0     .05       0   230.2      .1       0   278.3    .045       0
  301.16      .1       0   572.2     .04       0   850.7      .1       0
#XS Ineff= 2 , 0
                          575.26         2431.02
Permanent Ineff=
       F       F
Bank Sta=278.3,301.16
XS Rating Curve= 0 ,0
Exp/Cntr(USF)=0,0
Exp/Cntr=0.3,0.1

Type RM Length L Ch R = 1 ,20130   ,328.2,332,323
XS GIS Cut Line= 4
2079817.20896267331390.4425105572079290.28613141331381.971082402
2079149.66042402331182.045377933 2077660.3833543331244.733946283
#Sta/Elev= 30
       0 2455.68    44.9 2452.19  166.852437.165   205.7 2434.12   218.8 2430.67
   235.2 2430.58  266.932426.814   281.1  2424.7     291 2425.15   333.6 2423.47
   340.2 2424.69   366.4 2425.86  435.732425.359  582.392425.181   731.82425.024
   761.3 2422.75   775.4 2424.87  899.912424.738   949.4 2424.82   962.6 2429.81
   975.7 2432.52   991.2 2432.43  1005.2 2434.41  1057.3 2423.88 1123.742424.642
 1428.282427.296 1655.52 2429.02 1690.092429.362  2063.72432.993    2262 2432.95
#Mann= 14 ,-1 , 0
       0     .05       0  166.85     .06       0  266.93      .1       0
     291    .045       0   340.2      .1       0  435.73      .1       0
  582.39    .025       0   731.8      .1       0  899.91      .1       0
 1123.74      .1       0 1428.28      .1       0 1655.52      .1       0
 1690.09      .1       0  2063.7      .1       0
#XS Ineff= 2 , 0
                          567.49          2434.7
Permanent Ineff=
       F       F
Bank Sta=291,340.2
XS Rating Curve= 0 ,0
Exp/Cntr(USF)=0,0
Exp/Cntr=0.3,0.1

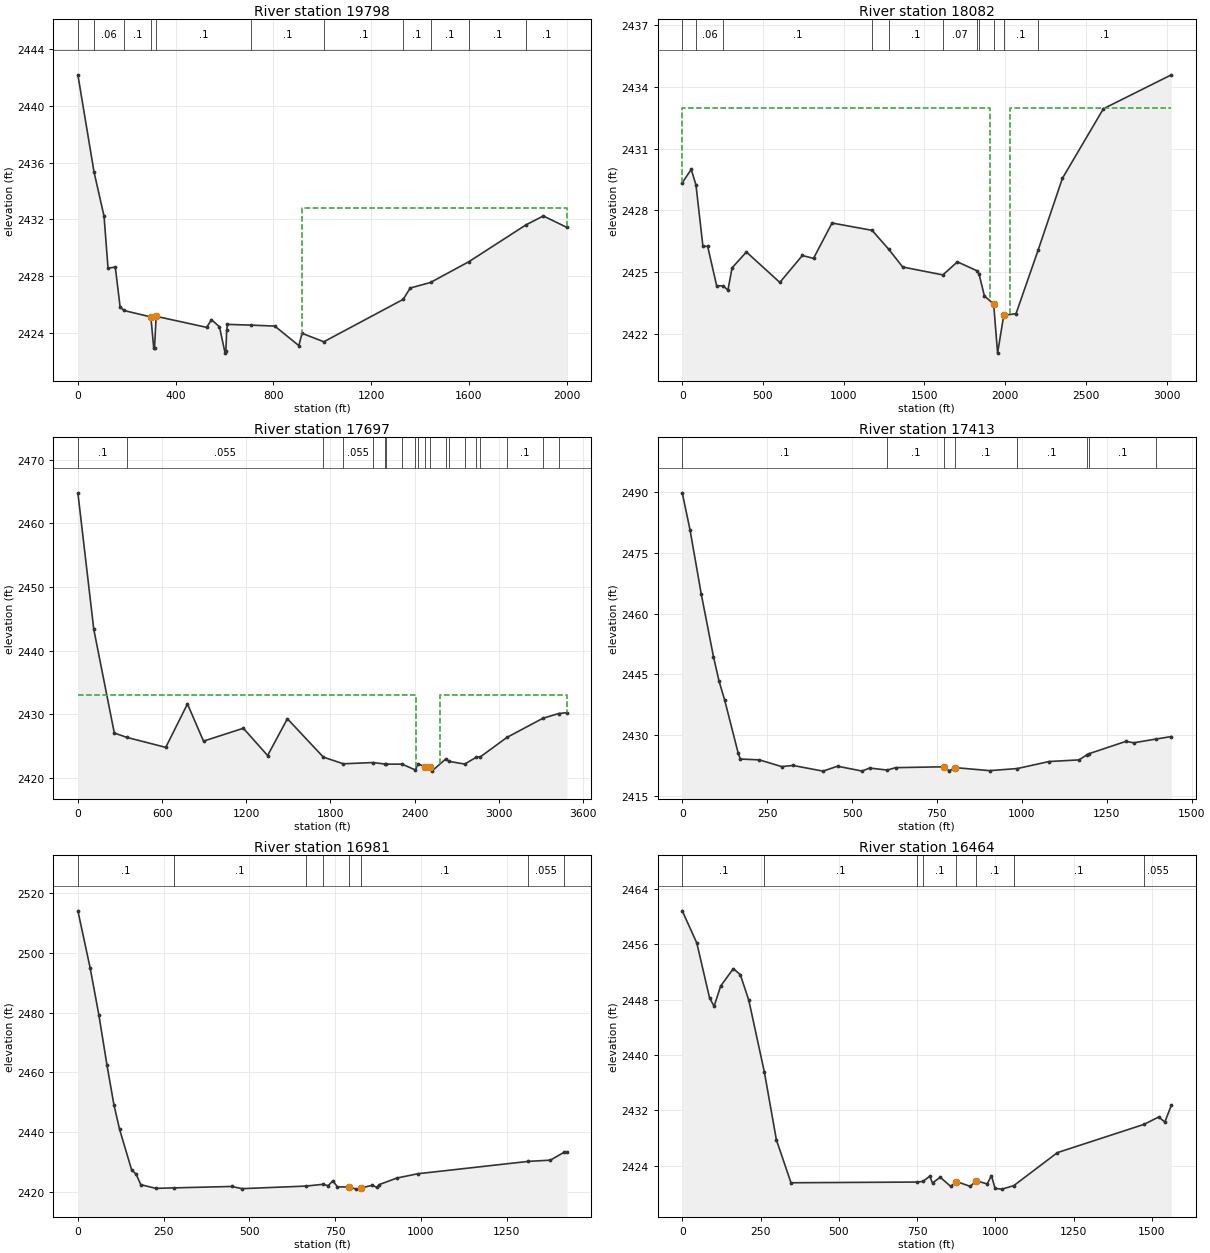
Type RM Length L Ch R = 1 ,19798   ,1700.4,1716.3,1747
XS GIS Cut Line= 2
2079748.24526236331106.0744469192077746.47816488331116.533000197
#Sta/Elev= 30
       0 2442.21   66.24 2435.34   107.1 2432.22   123.5 2428.55   153.1 2428.63
   172.8 2425.83   187.92425.564  298.722425.106   310.6 2422.89   313.8 2422.93
   320.4 2425.15   527.1 2424.37   546.8 2424.91   579.6 2424.41   602.6 2422.55
   605.8 2422.69   609.1 2424.18   612.4 2424.58  707.62 2424.53     806 2424.46
   904.4 2423.08   917.5 2423.95 1006.652423.353 1331.242426.346  1360.4 2427.15
  1443.42427.542  1600.4 2429.01 1833.872431.609  1905.1 2432.24  2001.8 2431.43
#Mann= 11 ,-1 , 0
       0     .05       0   66.24     .06       0   187.9      .1       0
  298.72    .045       0   320.4      .1       0  707.62      .1       0
 1006.65      .1       0 1331.24      .1       0  1443.4      .1       0
  1600.4      .1       0 1833.87      .1       0
#XS Ineff= 2 , 0
                          915.63         2432.77
Permanent Ineff=
       F       F
Bank Sta=298.72,320.4
XS Rating Curve= 0 ,0
Exp/Cntr(USF)=0,0
Exp/Cntr=0.5,0.3

Type RM Length L Ch R = 1 ,18082   ,378.5,384.3,369.4
XS GIS Cut Line= 4
2079818.09721324330994.5849560122079229.18008459330966.176719421
2078516.41641071330866.117106712 2076884.4383662330322.353137515
#Sta/Elev= 30
       0 2429.35    55.7    2430   84.982429.243   127.9 2426.27   157.6 2426.25
   213.3 2424.33  253.562424.335   282.9 2424.12   308.6 2425.21   397.3 2425.98
   604.5  2424.5   743.9 2425.81     813 2425.67   927.9 2427.39 1175.892427.034
 1279.872426.105  1365.4 2425.25 1614.352424.865  1704.3  2425.5 1827.042425.063
 1838.222424.907  1871.7 2423.84    1929 2423.45  1953.2 2421.06  1991.3  2422.9
  2067.4 2422.98 2204.822426.082  2354.4 2429.56  2608.6 2432.95  3029.5  2434.6
#Mann= 11 ,-1 , 0
       0     .05       0   84.98     .06       0  253.56      .1       0
 1175.89     .07       0 1279.87      .1       0 1614.35     .07       0
 1827.04    .055       0 1838.22      .1       0    1929    .045       0
  1991.3      .1       0 2204.82      .1       0
#XS Ineff= 2 , 0
         1903.69    2433 2032.84            2433
Permanent Ineff=
       F       F
Bank Sta=1929,1991.3
XS Rating Curve= 0 ,0
Exp/Cntr(USF)=0,0
Exp/Cntr=0.5,0.3

Type RM Length L Ch R = 1 ,17697   ,304.4,284.2,289.4
XS GIS Cut Line= 6
 2080074.6941008330193.1033111092079871.80318729330602.713268577
2079435.39631672330640.9945730132078979.84879393 330606.54139902
2078282.21737565330418.1133285372076939.45526747329986.384267153
#Sta/Elev= 30
       0 2464.77   113.3 2443.36   259.7 2427.07  348.942426.388   626.1 2424.82
   780.9 2431.64   895.2  2425.8  1179.2 2427.82    1352 2423.54  1492.9 2429.31
 1749.282423.287 1891.212422.244 2104.042422.436 2188.572422.198 2198.622422.185
 2310.142422.188  2405.72421.263 2421.66 2422.22  2476.9 2421.79  2512.4  2421.8
    2522 2421.09 2622.832423.023  2644.72422.617 2756.23  2422.2 2839.962423.284
 2867.752423.328 3057.112426.378 3313.84 2429.39 3425.362430.123  3485.1 2430.27
#Mann= 20 ,-1 , 0
       0      .1       0  348.94    .055       0 1749.28      .1       0
 1891.21    .055       0 2104.04    .035       0 2188.57      .1       0
 2198.62     .05       0 2310.14    .035       0  2405.7      .1       0
 2421.66    .055       0  2476.9    .045       0  2512.4    .055       0
 2622.83      .1       0  2644.7     .06       0 2756.23    .035       0
 2839.96      .1       0 2867.75    .055       0 3057.11      .1       0
 3313.84    .055       0 3425.36    .035       0
#XS Ineff= 2 , 0
            2411    2433    2577            2433
Permanent Ineff=
       F       F
Bank Sta=2476.9,2512.4
XS Rating Curve= 0 ,0
Exp/Cntr(USF)=0,0
Exp/Cntr=0.5,0.3

Type RM Length L Ch R = 1 ,17413   ,437.7,432.6,424.8
XS GIS Cut Line= 2
2078489.29843105330124.1340227642077053.89823756330006.589439989
#Sta/Elev= 30
       0 2489.78    22.8 2480.69    55.7 2464.93    91.9 2449.36   108.4 2443.31
   124.9 2438.65   164.6 2425.59   170.9 2424.09   226.9 2423.89   292.7 2422.23
   325.9 2422.51   414.5 2421.11   457.3 2422.32   529.3 2421.13   551.8 2421.87
  603.542421.374   628.5 2421.97   770.5 2422.18   786.5 2421.19     803 2421.98
     905 2421.23  986.782421.751    1080 2423.48  1168.4 2423.88 1191.432425.141
 1196.31 2425.37  1306.6 2428.46  1329.5  2428.1 1396.092429.043  1440.2 2429.64
#Mann= 8 ,-1 , 0
       0      .1       0  603.54      .1       0   770.5    .045       0
     803      .1       0  986.78      .1       0 1191.43    .055       0
 1196.31      .1       0 1396.09    .055       0
Bank Sta=770.5,803
XS Rating Curve= 0 ,0
Exp/Cntr(USF)=0,0
Exp/Cntr=0.3,0.1

Type RM Length L Ch R = 1 ,16981   ,518.6,516.6,480.9
XS GIS Cut Line= 2
2078161.32049481329643.699723085 2076783.1935351330008.903367407
#Sta/Elev= 30
       0 2513.99    35.9 2494.86      61 2479.35    84.7 2462.56   105.1  2449.2
   121.7 2440.96   156.6  2427.5   169.6 2426.06   183.5 2422.52   227.3 2421.29
  280.142421.446   447.9 2421.92   478.6 2421.19  664.282422.045  714.532422.638
   729.6 2422.18   743.2 2423.79   756.7 2421.79   791.52421.739   811.3 2421.03
     825 2421.43   858.6 2422.32   872.1 2421.58   878.9 2422.56   929.8 2424.73
   990.9 2426.17 1313.41  2430.3  1377.4 2430.71 1416.31 2433.28  1425.7 2433.49
#Mann= 8 ,-1 , 0
       0      .1       0  280.14      .1       0  664.28     .07       0
  714.53      .1       0   791.5    .045       0     825      .1       0
 1313.41    .055       0 1416.31    .035       0
Bank Sta=791.5,825
XS Rating Curve= 0 ,0
Exp/Cntr(USF)=0,0
Exp/Cntr=0.3,0.1

Type RM Length L Ch R = 1 ,16464   ,438.9,440.6,397.3
XS GIS Cut Line= 2
2077847.79661147328906.4017996432076703.95123492329971.004876015
#Sta/Elev= 30
       0 2460.82    46.6 2456.16    87.4 2448.22   101.8 2447.05   122.8 2449.97
   163.1 2452.47   185.5 2451.61   212.6 2447.91  262.522437.502   300.7 2427.77
   347.4 2421.56     7502421.662  769.242421.755   790.6  2422.5   799.6 2421.53
   824.1 2422.36   857.8 2421.03   875.8 2421.74   920.5 2421.03   938.5 2421.84
   974.4  2421.4   987.8 2422.59   999.5 2420.74  1021.6 2420.64 1059.192421.144
  1198.5 2425.91 1475.462429.993  1522.4 2431.06  1541.7 2430.32  1562.6 2432.75
#Mann= 8 ,-1 , 0
       0      .1       0  262.52      .1       0     750     .07       0
  769.24      .1       0   875.8    .045       0   938.5      .1       0
 1059.19      .1       0 1475.46    .055       0
Bank Sta=875.8,938.5
XS Rating Curve= 0 ,0
Exp/Cntr(USF)=0,0
Exp/Cntr=0.3,0.1

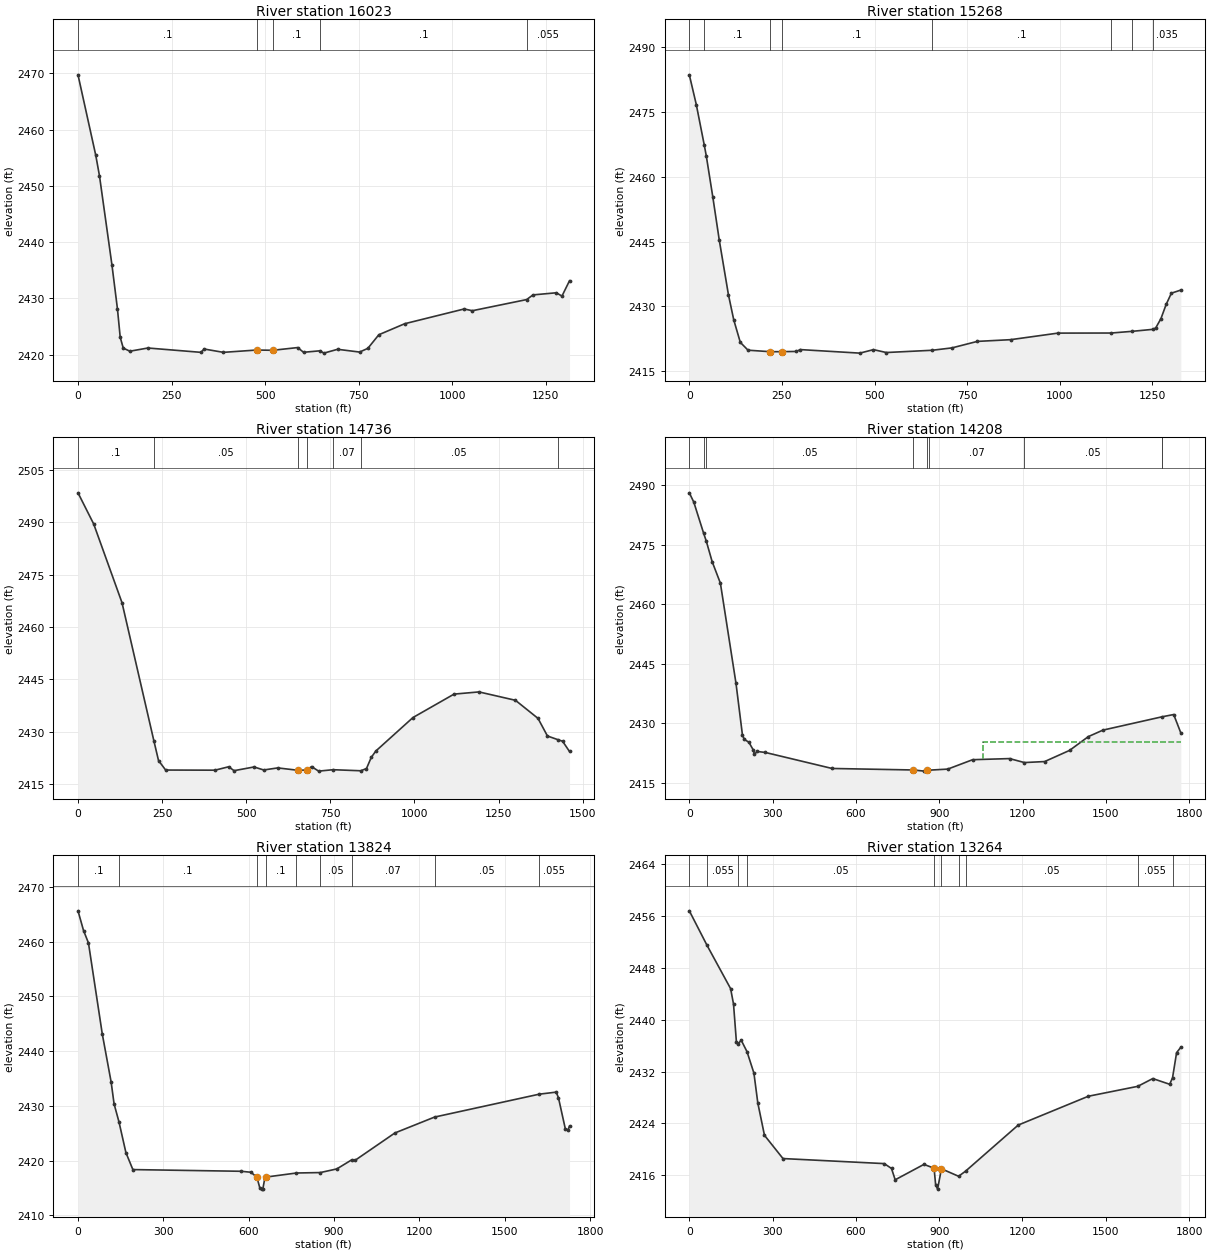
Type RM Length L Ch R = 1 ,16023   ,748.1,755.8,735.5
XS GIS Cut Line= 2
2077176.62134246328763.5580753232076584.37128152329935.655054552
#Sta/Elev= 30
       0 2469.75    47.6 2455.41    57.4 2451.79    90.7 2435.95   105.4 2428.15
   112.8 2423.09   120.9 2421.17   138.5 2420.61   186.8 2421.18   328.5 2420.41
     337    2421   388.5 2420.41   477.4 2420.82   520.82420.776     587 2421.26
   602.5 2420.42  646.792420.685   656.8 2420.27   693.6 2420.95   752.4 2420.46
   774.4 2421.12   803.8 2423.54     873  2425.5  1031.7 2428.12  1053.6 2427.81
 1198.752429.793  1215.5 2430.62    1278    2431    1293 2430.41  1313.2 2433.14
#Mann= 5 ,-1 , 0
       0      .1       0   477.4    .045       0   520.8      .1       0
  646.79      .1       0 1198.75    .055       0
Bank Sta=477.4,520.8
XS Rating Curve= 0 ,0
Exp/Cntr(USF)=0,0
Exp/Cntr=0.3,0.1

Type RM Length L Ch R = 1 ,15268   ,526.9,532.1,525.7
XS GIS Cut Line= 2
2076575.06892455328552.7046504882076088.24557603329786.817342904
#Sta/Elev= 30
       0 2483.66    18.8 2476.78   40.552467.287    45.7 2464.92    63.3  2455.4
    80.9 2445.31   105.6 2432.67   119.9 2426.86   137.6 2421.64   158.5 2419.82
   218.5 2419.47   248.9 2419.48     289 2419.53   299.5 2419.96   460.2 2419.14
   497.1 2419.95   531.7 2419.28  655.272419.801   708.7 2420.35   777.4 2421.86
   867.4 2422.26     995 2423.78 1138.812423.801 1195.932424.198 1251.852424.659
  1258.9 2424.98    1273 2427.14  1287.1 2430.44  1301.2 2433.04  1326.7 2433.76
#Mann= 8 ,-1 , 0
       0      .1       0   40.55      .1       0   218.5    .045       0
   248.9      .1       0  655.27      .1       0 1138.81    .055       0
 1195.93     .06       0 1251.85    .035       0
Bank Sta=218.5,248.9
XS Rating Curve= 0 ,0
Exp/Cntr(USF)=0,0
Exp/Cntr=0.3,0.1

Type RM Length L Ch R = 1 ,14736   ,518.1,527.1,524.7
XS GIS Cut Line= 3
2076399.22250403328395.987801747 2076166.3852763328450.241136363
2075768.52748911329605.385052574
#Sta/Elev= 30
       0 2498.43    46.7  2489.5   130.9 2466.95  225.572427.409   239.3 2421.79
   260.5 2419.06   407.1 2419.02   447.9    2420   463.8 2418.88   523.2 2419.94
     552 2419.08   593.6 2419.67     6542418.993  679.24 2419.06   694.3 2420.05
   715.1 2418.75  758.152419.155  840.462418.853   857.4 2419.49   871.6 2422.68
   885.1  2424.5   995.5 2434.09  1117.6  2440.8  1191.7 2441.43  1300.1 2439.03
  1367.2 2433.85  1395.2 2428.81  1425.72427.776  1440.3  2427.3  1460.8 2424.37
#Mann= 7 ,-1 , 0
       0      .1       0  225.57     .05       0     654    .045       0
  679.24     .05       0  758.15     .07       0  840.46     .05       0
  1425.7    .055       0
Bank Sta=654,679.24
XS Rating Curve= 0 ,0
Exp/Cntr(USF)=0,0
Exp/Cntr=0.3,0.1

Type RM Length L Ch R = 1 ,14208   ,380.6,384,378
XS GIS Cut Line= 3
2075944.85082662327808.2433434012075904.16082565328140.545017927
2075246.33914343329415.498381416
#Sta/Elev= 30
       0 2488.07    16.1 2485.73   51.622477.867   61.112475.897    82.2 2470.73
   111.9  2465.3   168.1 2440.03   191.3 2427.03   197.9 2425.95   214.4 2425.23
   230.9  2423.2   234.2 2422.15   244.1 2422.91   273.9 2422.65   513.9 2418.62
   805.8 2418.24   846.4 2417.95   856.9 2418.15   861.12418.185   930.3 2418.46
  1019.9 2420.83  1152.8 2421.11 1206.262420.109  1279.1 2420.36  1368.7 2423.17
  1436.5 2426.65  1488.8 2428.28 1700.682431.623  1743.7 2432.21  1769.4 2427.57
#Mann= 9 ,-1 , 0
       0     .05       0   51.62      .1       0   61.11     .05       0
   805.8    .045       0   856.9     .05       0   861.1     .07       0
 1206.26     .05       0 1700.68    .035       0 1700.68    .055       0
#XS Ineff= 2 , 0
                         1058.54         2425.17
Permanent Ineff=
       F       F
Bank Sta=805.8,856.9
XS Rating Curve= 0 ,0
Exp/Cntr(USF)=0,0
Exp/Cntr=0.3,0.1

Type RM Length L Ch R = 1 ,13824   ,552,560.4,555.2
XS GIS Cut Line= 2
2075644.83322675327743.3995934022075090.96844416329380.037838921
#Sta/Elev= 30
       0 2465.65    19.5 2462.05    36.8 2459.78    85.3 2443.18   116.5 2434.38
   126.9 2430.37  144.16 2427.07   168.4 2421.49   192.9 2418.38   573.7 2418.07
   608.3 2417.89   629.1 2416.95   639.5 2414.97   646.4 2414.81   649.9 2414.88
   656.8 2416.82   660.3 2417.01  767.952417.756  851.762417.836   909.8  2418.5
  961.762420.146   975.4 2420.12    1114 2425.07 1253.332427.971 1621.722432.159
    1681 2432.53  1688.9 2431.51  1713.2  2425.8  1722.4 2425.63  1727.8 2426.33
#Mann= 9 ,-1 , 0
       0      .1       0  144.16      .1       0   629.1    .045       0
   660.3      .1       0  767.95      .1       0  851.76     .05       0
  961.76     .07       0 1253.33     .05       0 1621.72    .055       0
Bank Sta=629.1,660.3
XS Rating Curve= 0 ,0
Exp/Cntr(USF)=0,0
Exp/Cntr=0.3,0.1

Type RM Length L Ch R = 1 ,13264   ,195.1,195.2,194.3
XS GIS Cut Line= 2
 2075257.1109879327327.2431500622074640.17867312328986.814642795
#Sta/Elev= 30
       0 2456.81   64.052451.461   148.7  2444.8   159.2 2442.42   169.7 2436.52
  175.822436.321   187.2 2436.81  207.852435.058   232.7 2431.75   246.7 2427.15
   270.7 2422.15   337.4 2418.56   702.3 2417.78   728.3 2417.03   741.5 2415.28
   845.1 2417.66  881.63 2417.07   887.2 2414.55   894.2 2413.84   908.2 2416.98
  970.012415.824  995.022416.613  1184.7 2423.73  1437.2 2428.18 1615.152429.709
  1669.4 2430.91  1730.2 2430.03 1740.582431.025  1755.2 2434.91  1770.5 2435.75
#Mann= 10 ,-1 , 0
       0      .1       0   64.05    .055       0  175.82     .06       0
  207.85     .05       0  881.63    .045       0   908.2     .05       0
  970.01     .07       0  995.02     .05       0 1615.15    .055       0
 1740.58    .035       0
Bank Sta=881.63,908.2
XS Rating Curve= 0 ,0
Exp/Cntr(USF)=0,0
Exp/Cntr=0.5,0.3