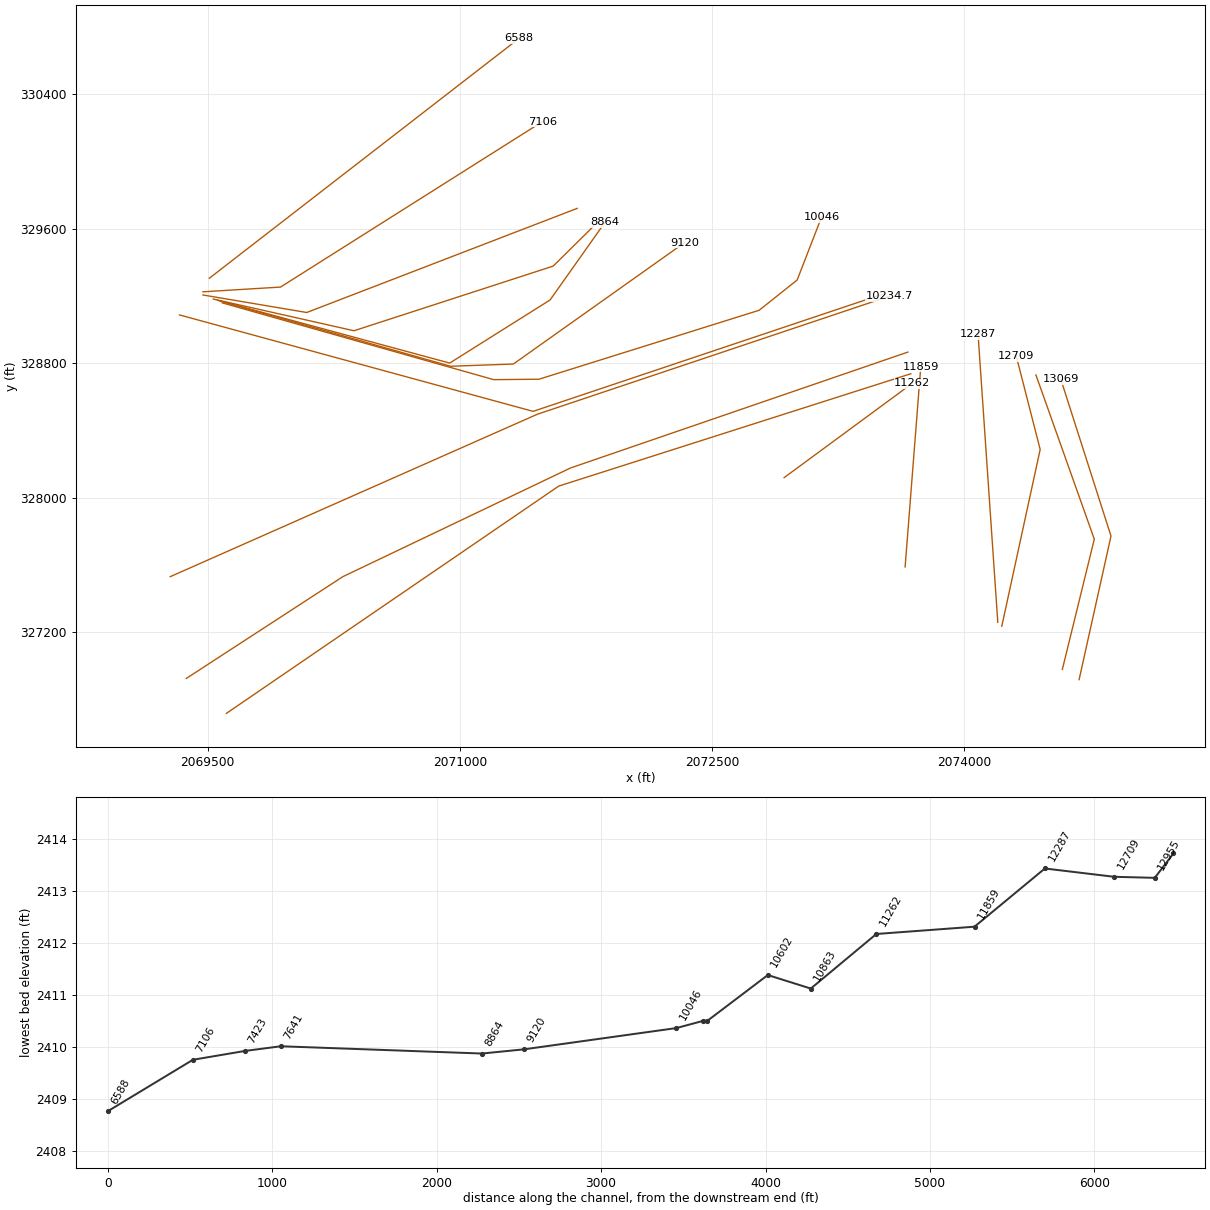
HEC-RAS study OTTERCK.prj: OTTERCK

--- OTTERCK.g01 (geometry) --- (continued)

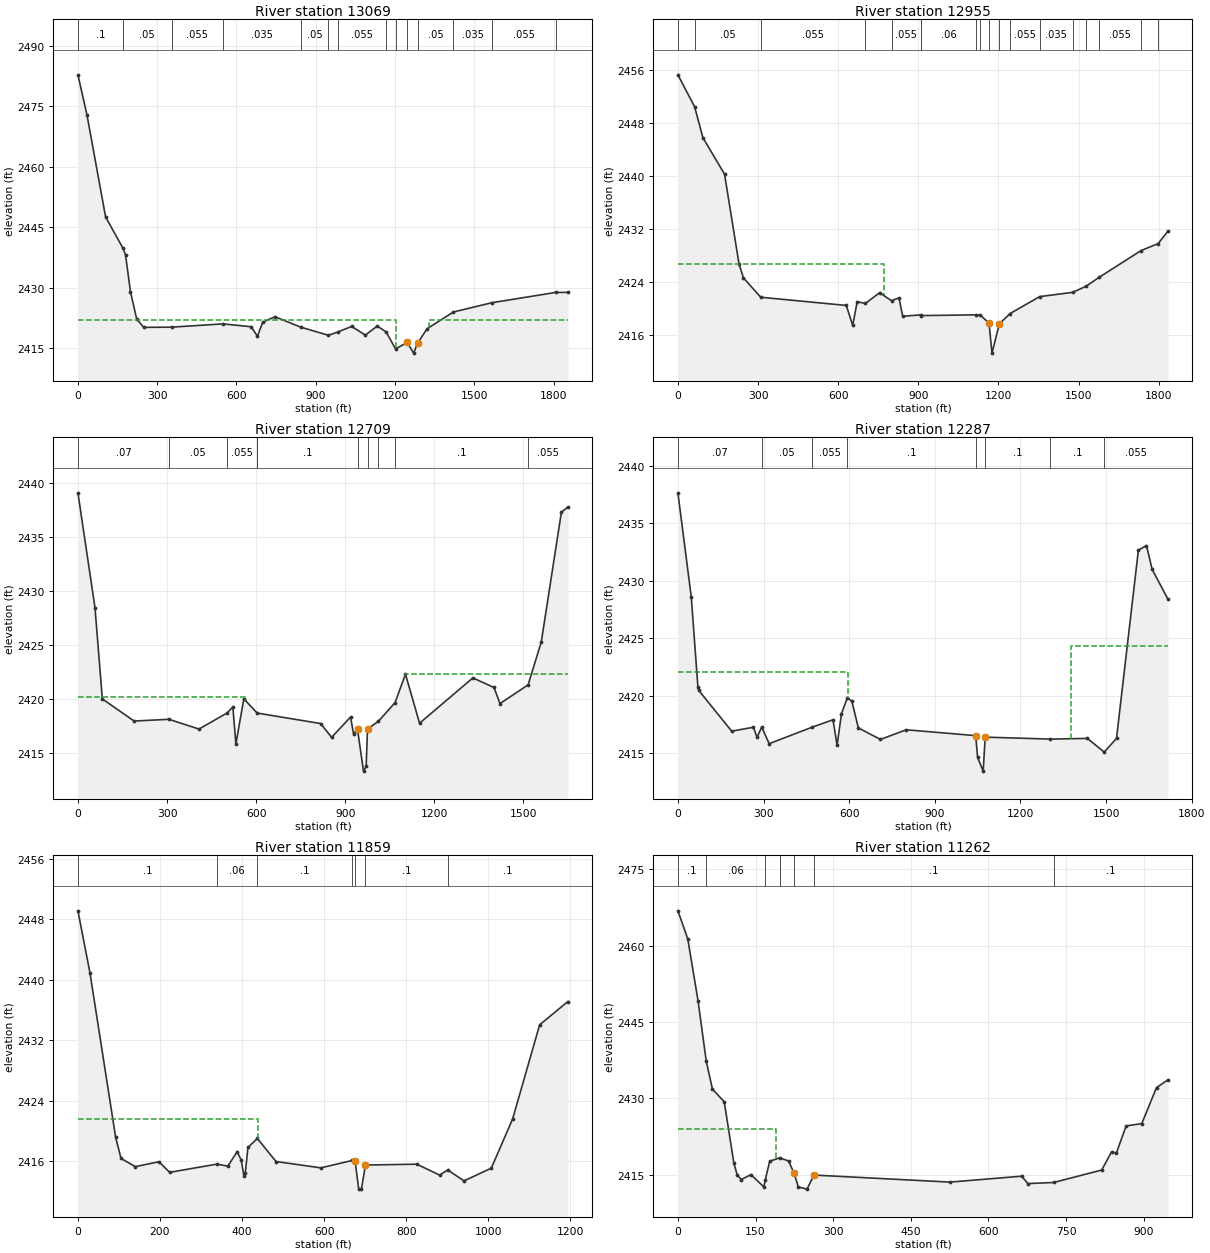
Type RM Length L Ch R = 1 ,13069   ,112.4,113.7,114.1
XS GIS Cut Line= 3
2074682.85195044326918.0485035172074872.46499351327772.035881955
2074573.81465219328705.372365415
#Sta/Elev= 30
       0 2482.75    34.3 2472.79   104.8  2447.5  170.912439.698   180.1 2438.14
   198.9 2428.96   222.5 2422.18   249.3 2420.12  354.352420.173  549.782420.984
   655.8 2420.27   679.5 2417.91   699.7 2421.43   745.9 2422.75  842.912420.187
  948.27 2418.15  983.072418.957  1036.3 2420.36    1088 2418.19  1132.8 2420.45
  1166.42418.992 1202.152414.778  1246.4 2416.37  1270.6 2413.73  1285.6 2416.22
  1321.7 2419.79 1421.26 2423.93  1566.52426.227 1807.76 2428.78  1854.7 2428.79
#Mann= 14 ,-1 , 0
       0      .1       0  170.91     .05       0  354.35    .055       0
  549.78    .035       0  842.91     .05       0  948.27    .055       0
  983.07    .055       0  1166.4     .07       0 1202.15     .06       0
  1246.4    .045       0  1285.6     .05       0 1421.26    .035       0
  1566.5    .055       0 1807.76     .05       0
#XS Ineff= 2 , 0
         1204.43    2422 1328.41            2422
Permanent Ineff=
       F       F
Bank Sta=1246.4,1285.6
XS Rating Curve= 0 ,0
Exp/Cntr(USF)=0,0
Exp/Cntr=0.5,0.3

Type RM Length L Ch R = 1 ,12955   ,250.6,246.5,232.5
XS GIS Cut Line= 3
2074583.16743369326978.7794961262074773.23985241327753.431167999
2074425.95185856328730.178650689
#Sta/Elev= 30
       0 2455.28   62.56 2450.46    93.5  2445.8   174.7 2440.27   228.6 2426.76
   245.5 2424.61  310.132421.699   630.3 2420.46   654.3 2417.46   671.2 2421.03
  701.632420.755     755 2422.38  799.75 2421.17   827.5 2421.61   841.4 2418.82
  908.642419.035  910.642418.926  1114.9 2419.04 1132.422418.968  1164.5 2417.81
  1175.7 2413.26  1203.1 2417.67 1243.322419.235 1354.212421.795  1478.32422.442
 1527.41 2423.35    15762424.687 1733.642428.743 1797.782429.802  1834.3 2431.68
#Mann= 18 ,-1 , 0
       0      .1       0   62.56     .05       0  310.13    .055       0
  701.63    .035       0  799.75    .055       0  908.64     .07       0
  910.64     .06       0  1114.9      .1       0 1132.42     .06       0
  1164.5    .045       0  1203.1     .06       0 1243.32    .055       0
 1354.21    .035       0  1478.3    .055       0 1527.41      .1       0
    1576    .055       0 1733.64      .1       0 1797.78    .055       0
#XS Ineff= 2 , 0
          770.48 2426.73
Permanent Ineff=
       F       F
Bank Sta=1164.5,1203.1
XS Rating Curve= 0 ,0
Exp/Cntr(USF)=0,0
Exp/Cntr=0.5,0.3

Type RM Length L Ch R = 1 ,12709   ,407.1,421.7,416.5
XS GIS Cut Line= 3
2074222.96300563327235.7282821492074451.27912214328286.886640345
2074308.86411877328842.983320165
#Sta/Elev= 30
       0 2439.07    57.4 2428.44    82.2 2419.97   189.2 2417.92  306.162418.083
   407.5 2417.18  501.532418.656   521.6 2419.22   531.8 2415.79   558.5 2419.98
   603.6 2418.66   817.1 2417.69     854 2416.41   917.8 2418.29   927.8 2416.75
   941.3 2417.14   961.4 2413.28   970.4 2413.72   974.9 2417.19 1011.152417.888
 1067.592419.629  1102.7 2422.26  1150.1 2417.72  1329.6 2421.92  1400.7 2421.03
  1420.9 2419.54  1515.4 2421.27  1559.9 2425.25  1627.6 2437.28  1649.7 2437.75
#Mann= 10 ,-1 , 0
       0     .07       0  306.16     .05       0  501.53    .055       0
   603.6      .1       0   603.6      .1       0   941.3    .045       0
   974.9      .1       0 1011.15    .035       0 1067.59      .1       0
  1515.4    .055       0
#XS Ineff= 2 , 0
          564.33 2420.17 1101.05         2422.29
Permanent Ineff=
       F       F
Bank Sta=941.3,974.9
XS Rating Curve= 0 ,0
Exp/Cntr(USF)=0,0
Exp/Cntr=0.3,0.1

Type RM Length L Ch R = 1 ,12287   ,429.5,427.9,426
XS GIS Cut Line= 2
2074199.21169239327258.951558596 2074081.8561427328971.788041134
#Sta/Elev= 30
       0 2437.67      47 2428.57      70 2420.78    73.3 2420.46   188.4 2416.92
   264.7 2417.26   277.2 2416.38  293.612417.269   319.9 2415.83  471.252417.275
   543.5 2417.91   557.7 2415.68   573.1 2418.44  593.592419.816   609.3 2419.54
   632.3  2417.2   709.5  2416.2   800.1 2417.04  1043.4 2416.53    1050 2414.63
  1069.6 2413.44  1076.7  2416.4 1305.312416.228  1434.7 2416.29 1493.512415.096
  1536.7 2416.29  1613.3 2432.67  1641.6 2433.08  1661.6    2431  1716.9 2428.41
#Mann= 8 ,-1 , 0
       0     .07       0  293.61     .05       0  471.25    .055       0
  593.59      .1       0  1043.4    .045       0  1076.7      .1       0
 1305.31      .1       0 1493.51    .055       0
#XS Ineff= 2 , 0
          595.13 2422.03 1377.18         2424.37
Permanent Ineff=
       F       F
Bank Sta=1043.4,1076.7
XS Rating Curve= 0 ,0
Exp/Cntr(USF)=0,0
Exp/Cntr=0.3,0.1

Type RM Length L Ch R = 1 ,11859   ,600.4,596.9,568
XS GIS Cut Line= 2
2073647.96090851327588.1707767482073741.03118148328778.822321424
#Sta/Elev= 30
       0 2449.09    29.4 2440.88    91.9 2419.18   105.1 2416.37     140 2415.29
   197.3 2415.94   223.6 2414.54  339.512415.632   365.2 2415.35   388.1 2417.27
     398 2416.16   404.6 2414.04   407.9 2414.46   414.4 2417.83  437.312419.015
   482.7 2415.97   592.2 2415.13  668.312416.107   675.5 2416.04   684.3 2412.34
   690.9 2412.32   700.8  2415.5   825.8 2415.62   881.7 2414.17  901.162414.858
     941 2413.41  1007.5 2415.09  1059.5  2421.6  1125.3 2434.03  1194.3 2437.11
#Mann= 7 ,-1 , 0
       0      .1       0  339.51     .06       0  437.31      .1       0
  668.31      .1       0   675.5    .045       0   700.8      .1       0
  901.16      .1       0
#XS Ineff= 2 , 0
          439.26 2421.56
Permanent Ineff=
       F       F
Bank Sta=675.5,700.8
XS Rating Curve= 0 ,0
Exp/Cntr(USF)=0,0
Exp/Cntr=0.3,0.1

Type RM Length L Ch R = 1 ,11262   ,404.1,398.6,383.8
XS GIS Cut Line= 2
2072928.27238511  328119.3238758 2073691.0656573 328680.56608014
#Sta/Elev= 30
       0 2466.81    19.1 2461.29      39  2449.1   54.762437.315    66.7 2431.82
    89.5 2429.33   108.2 2417.28   114.4 2415.03   122.3 2414.06   141.1 2415.01
   166.3  2412.6  168.542413.885   177.4 2417.65  196.632418.317   213.8 2417.71
   224.3 2415.35   232.8 2412.61   249.4 2412.18   263.1 2414.94   525.8 2413.56
   664.2 2414.72   676.5 2413.27   726.12413.482     819 2415.93     838 2419.48
   847.4 2419.28   866.2 2424.59   896.4 2425.04   924.9 2432.11     947 2433.64
#Mann= 7 ,-1 , 0
       0      .1       0   54.76     .06       0  168.54      .1       0
  196.63      .1       0   224.3    .045       0   263.1      .1       0
   726.1      .1       0
#XS Ineff= 2 , 0
          189.67 2424.08
Permanent Ineff=
       F       F
Bank Sta=224.3,263.1
XS Rating Curve= 0 ,0
Exp/Cntr(USF)=0,0
Exp/Cntr=0.3,0.1

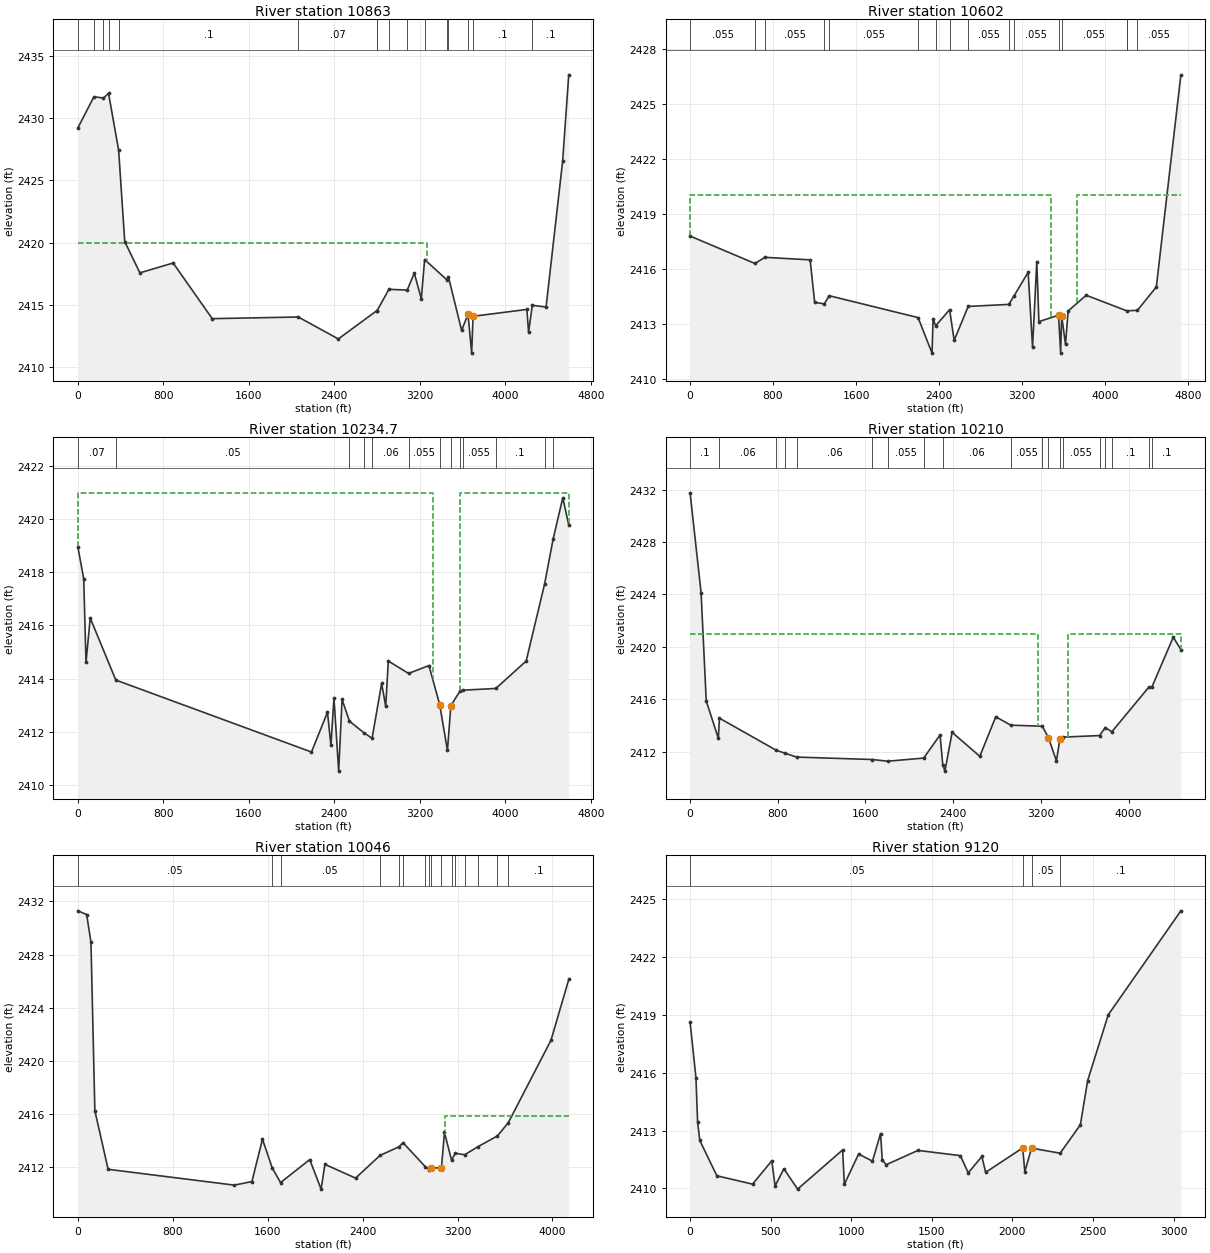
Type RM Length L Ch R = 1 ,10863   ,265.6,261.5,277.8
XS GIS Cut Line= 3
2069611.09264218326717.2023355312071587.66876606328069.025995657
2073682.04313273328737.402342611
#Sta/Elev= 30
       0 2429.24  149.352431.724  238.392431.629  286.482431.991  380.762427.432
   437.8 2420.09   579.6 2417.58     891 2418.37  1256.6  2413.9 2061.942414.032
  2436.6 2412.27 2798.562414.551 2798.992414.536 2910.072416.256 3081.412416.196
  3147.8 2417.56  3213.2 2415.49 3244.26 2418.65 3453.192417.012 3467.062417.257
  3590.5 2412.96  3650.5 2414.25  3684.5 2411.13  3697.6 2414.09  4201.4 2414.64
  4217.1 2412.81  4252.12414.974  4380.7 2414.83  4535.7 2426.53  4593.1 2433.49
#Mann= 16 ,-1 , 0
       0     .06       0  149.35    .035       0  238.39     .06       0
  286.48    .055       0  380.76      .1       0 2061.94     .07       0
 2798.56      .1       0 2798.99     .07       0 2910.07      .1       0
 3081.41    .055       0 3244.26     .06       0 3453.19    .055       0
 3467.06      .1       0  3650.5    .045       0  3697.6      .1       0
  4252.1      .1       0
#XS Ineff= 2 , 0
         3265.68 2419.94
Permanent Ineff=
       F       F
Bank Sta=3650.5,3697.6
XS Rating Curve= 0 ,0
Exp/Cntr(USF)=0,0
Exp/Cntr=0.5,0.3

Type RM Length L Ch R = 1 ,10602   ,362.7,367.3,366.8
XS GIS Cut Line= 4
 2069372.9556223326925.213176591 2070303.1913201327530.057786683
2071658.34949714328177.011831655 2073664.2898496328866.075311507
#Sta/Elev= 30
       0 2417.78  624.912416.284  721.832416.619  1157.6 2416.48  1201.2 2414.16
 1293.572414.078 1341.782414.523 2198.43 2413.33    2333 2411.39  2342.8 2413.24
 2368.552412.886 2502.292413.762  2546.3 2412.09  2681.52413.939 3073.092414.049
 3120.712414.486  3259.6  2415.8  3302.1  2411.7    3343 2416.39  3363.2 2413.11
 3552.75 2413.46  3572.7 2411.42  3583.1 2413.41  3619.8 2411.87  3645.5 2413.69
    3819 2414.55  4209.32413.702  4312.62413.725  4495.4    2415  4732.2 2426.58
#Mann= 16 ,-1 , 0
       0    .055       0  624.91     .07       0  721.83    .055       0
 1293.57    .035       0 1341.78    .055       0 2198.43     .07       0
 2368.55    .055       0 2502.29     .07       0  2681.5    .055       0
 3073.09      .1       0 3120.71    .055       0 3552.75    .045       0
  3583.1    .055       0  4209.3      .1       0  4209.3    .035       0
  4312.6    .055       0
#XS Ineff= 2 , 0
         3483.39    2420 3734.32            2420
Permanent Ineff=
       F       F
Bank Sta=3552.75,3583.1
XS Rating Curve= 0 ,0
Exp/Cntr(USF)=0,0
Exp/Cntr=0.5,0.3

Type RM Length L Ch R = 1 ,10234.7 ,24.2,24.3,24.3
XS GIS Cut Line= 3
2069276.87929927327530.2499661542071460.85503978328496.543569253
2073552.30560225329197.744905978
#Sta/Elev= 30
       0 2418.94    53.9 2417.76    75.4 2414.61   114.9 2416.28  354.272413.943
    2186 2411.23  2335.6 2412.73  2367.9 2411.48  2396.3 2413.27  2440.5 2410.51
  2472.2 2413.21 2541.352412.394 2677.382411.954 2753.262411.749  2842.7 2413.82
  2880.8 2412.95    2905 2414.66  3094.92414.192  3285.6 2414.49    33862413.018
  3458.6 2411.29  3490.72412.979 3575.322413.522 3600.912413.561 3912.042413.626
  4195.5 2414.66  4367.8 2417.56 4448.572419.272  4538.2 2420.81  4594.1 2419.79
#Mann= 13 ,-1 , 0
       0     .07       0  354.27     .05       0 2541.35     .06       0
 2677.38     .07       0 2753.26     .06       0  3094.9    .055       0
    3386    .045       0  3490.7    .035       0 3575.32    .055       0
 3600.91    .055       0 3912.04      .1       0  4367.8     .06       0
 4448.57      .1       0
#XS Ineff= 2 , 0
         3325.09    2421 3575.14            2421
Permanent Ineff=
       F       F
Bank Sta=3386,3490.7
XS Rating Curve= 0 ,0
Exp/Cntr(USF)=0,0
Exp/Cntr=0.3,0.1

Type RM Length L Ch R = 1 ,10210   ,157.7,164.3,156.1
XS GIS Cut Line= 3
2069332.17654377329087.0800806992071435.33323462328513.558106024
2073526.78379709329214.759442749
#Sta/Elev= 30
       0 2431.75   100.4 2424.13   147.3 2415.87   257.7 2413.02  267.912414.551
  786.482412.102  867.222411.875     9722411.582 1662.532411.396  1802.62411.267
 2131.492411.507  2280.7 2413.27 2305.122411.012    2325 2410.51  2390.7 2413.47
  2643.3 2411.64  2788.7 2414.66 2925.342414.017 3213.852413.937  3269.6 2413.06
  3342.3 2411.29  3374.3 2412.98 3398.622413.104 3735.352413.224 3788.512413.837
 3847.59 2413.51 4184.31 2416.91 4212.34 2416.91  4408.1 2420.73  4477.7 2419.79
#Mann= 19 ,-1 , 0
       0      .1       0  267.91     .06       0  786.48     .05       0
  867.22     .07       0     972     .06       0 1662.53     .05       0
  1802.6    .055       0 2131.49     .05       0 2305.12     .06       0
 2925.34    .055       0 3213.85    .035       0  3269.6    .045       0
  3374.3    .035       0 3398.62    .055       0 3735.35      .1       0
 3788.51    .055       0 3847.59      .1       0 4184.31     .06       0
 4212.34      .1       0
#XS Ineff= 2 , 0
         3175.09    2421 3450.14            2421
Permanent Ineff=
       F       F
Bank Sta=3269.6,3374.3
XS Rating Curve= 0 ,0
Exp/Cntr(USF)=0,0
Exp/Cntr=0.5,0.3

Type RM Length L Ch R = 1 ,10046   ,884.5,926.4,935.3
XS GIS Cut Line= 6
 2069586.4208863329158.870743878 2071201.0060613328702.121491848
2071470.39301845328704.7739633082072779.99171712329114.903790342
 2073005.8514133329294.8259211932073151.32037016329669.982704667
#Sta/Elev= 30
       0 2431.29    73.5 2431.01   109.7 2428.93   142.5 2416.27   254.2 2411.86
  1318.7 2410.67  1466.5 2410.94  1555.5 2414.12 1637.372411.971 1707.852410.862
  1954.1 2412.59  2049.6 2410.37  2081.9 2412.23  2340.2  2411.2 2546.692412.904
 2704.742413.546 2740.512413.859 2926.922412.068 2960.972411.839  2977.3 2411.95
  3064.3 2411.98  3089.7 2414.63 3149.112412.555 3181.442413.068 3260.212412.953
 3369.082413.547  3536.12414.369  3627.72415.365  3987.6 2421.56  4137.4 2426.13
#Mann= 16 ,-1 , 0
       0     .05       0 1637.37    .055       0 1707.85     .05       0
 2546.69      .1       0 2704.74     .05       0 2740.51      .1       0
 2926.92     .06       0 2960.97     .05       0  2977.3    .045       0
  3064.3     .05       0 3149.11     .06       0 3181.44      .1       0
 3260.21     .05       0 3369.08      .1       0  3536.1     .06       0
  3627.7      .1       0
#XS Ineff= 2 , 0
                         3095.94         2415.87
Permanent Ineff=
       F       F
Bank Sta=2977.3,3064.3
XS Rating Curve= 0 ,0
Exp/Cntr(USF)=0,0
Exp/Cntr=0.5,0.3

Type RM Length L Ch R = 1 ,9120    ,249.4,255.9,244.8
XS GIS Cut Line= 4
2069573.23997725329169.7489750442070944.18149977328781.829145597
2071317.78895756328795.0370806312072334.84683687329516.311361318
#Sta/Elev= 30
       02418.634  36.457 2415.74  46.6862413.437  60.3242412.488 166.0232410.655
  387.65 2410.22 506.9882411.431 527.4462410.125     5822411.016 667.2412409.961
 946.8322411.997 957.0612410.2091045.7122411.7831131.6722411.4131182.0982412.846
1192.3272411.4961216.1942411.2251413.9542411.9711676.986  2411.71726.2292410.804
1810.4842411.6561833.9992410.832 2063.94  2412.12077.0042410.8672118.7422412.089
 2296.512411.8262421.845  2413.32467.0222415.5952594.7962419.0093045.4622424.407
#Mann= 4 ,-1 , 0
       0     .05       0 2063.94    .045       02118.742     .05       0
 2296.51      .1       0
Bank Sta=2063.94,2118.742
XS Rating Curve= 0 ,0
Exp/Cntr(USF)=0,0
Exp/Cntr=0.3,0.1

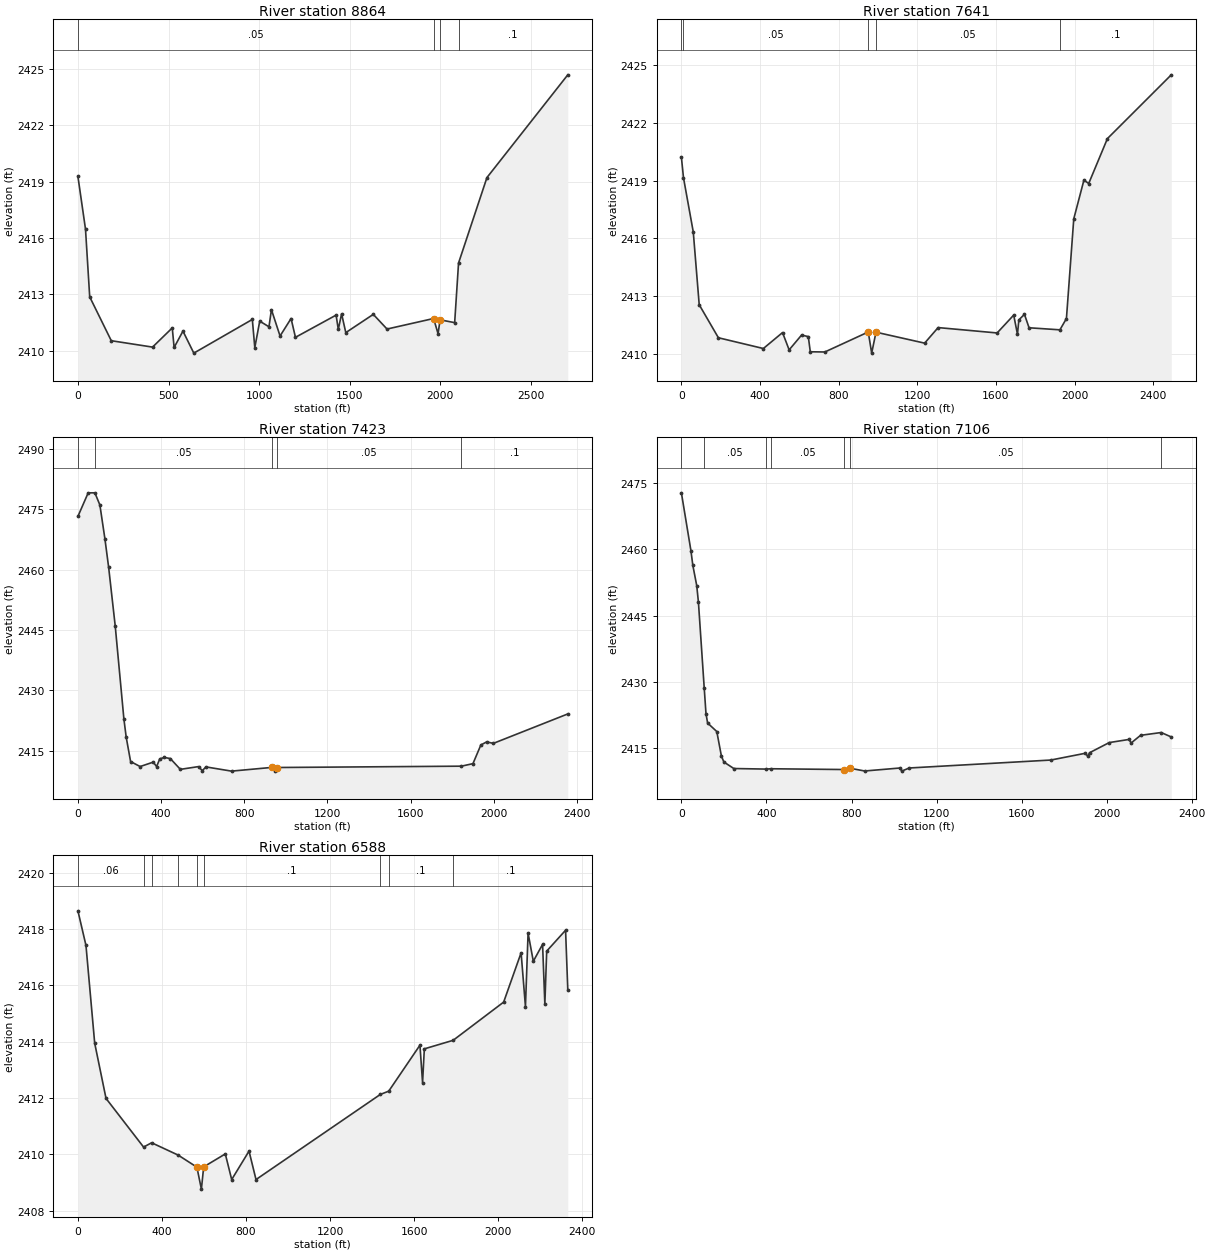
Type RM Length L Ch R = 1 ,8864    ,1177.3,1223.3,1196.9
XS GIS Cut Line= 4
2069558.58475046329174.3190029192070939.27820513328800.714624204
2071536.20051925329176.079883083  2071863.958477 329639.33554404
#Sta/Elev= 30
       0 2419.27    41.9 2416.47    65.1 2412.87   184.1 2410.54   411.8  2410.2
   520.6 2411.22   530.8 2410.18   579.6 2411.05   639.5 2409.88   962.4 2411.67
     976 2410.17  1003.2 2411.58  1054.2 2411.28  1067.8 2412.19  1115.4 2410.79
  1176.1 2411.72  1200.3 2410.72  1424.6  2411.9  1436.7 2411.14  1454.9 2411.97
  1478.1 2410.97  1629.8 2411.94  1705.6 2411.16  1962.6 2411.72  1987.2 2410.91
  1998.3 2411.65  2078.8  2411.5 2100.232414.669  2256.9 2419.21    2703 2424.67
#Mann= 4 ,-1 , 0
       0     .05       0  1962.6    .045       0  1998.3     .05       0
 2100.23      .1       0
Bank Sta=1962.6,1998.3
XS Rating Curve= 0 ,0
Exp/Cntr(USF)=0,0
Exp/Cntr=0.3,0.1

Type RM Length L Ch R = 1 ,7641    ,216.7,217.6,217
XS GIS Cut Line= 4
2069533.03177187329181.5730332132070369.82164166328992.974878752
2071554.51101968329377.4953878472071830.99957622  329650.3218443
#Sta/Elev= 30
       0 2420.22   10.662419.151    60.4 2416.33    90.6 2412.54   188.2 2410.82
   416.9 2410.26   514.4 2411.09     548 2410.19   611.2 2410.96   645.5 2410.88
   655.6 2410.09   729.6 2410.08   950.4 2411.12   967.8 2410.02  989.84 2411.11
  1237.1 2410.54  1305.8 2411.35  1605.9 2411.07  1690.2    2412  1709.4    2411
  1716.3 2411.75  1744.9 2412.04  1768.3 2411.34 1925.252411.233  1958.4 2411.82
  1995.7 2417.01  2047.4 2419.03  2071.6 2418.85  2166.9 2421.19  2491.7 2424.51
#Mann= 5 ,-1 , 0
       0     .06       0   10.66     .05       0   950.4    .045       0
  989.84     .05       0 1925.25      .1       0
Bank Sta=950.4,989.84
XS Rating Curve= 0 ,0
Exp/Cntr(USF)=0,0
Exp/Cntr=0.3,0.1

Type RM Length L Ch R = 1 ,7423    ,302.4,316.8,314.5
XS GIS Cut Line= 3
2069471.55682566329205.728797157 2070088.9316302329101.537017783
2071697.54482679 329720.85997609
#Sta/Elev= 30
       0 2473.26    49.4 2479.12   81.672479.125   105.7  2476.1   129.9 2467.69
   147.9 2460.58   179.6 2445.97   221.2 2422.88   232.3 2418.37   253.4 2412.32
   299.2 2411.07   362.5 2412.17   378.5 2411.06   393.7 2412.97   415.3 2413.33
   444.4 2413.06   492.8 2410.37   580.6 2411.06   598.2 2410.03   615.8 2410.98
   738.9 2409.93   932.4 2410.85   946.3 2410.06   957.1 2410.83 1844.632411.162
  1900.3 2411.79  1938.3 2416.43  1966.2  2417.2  1998.4 2416.83  2356.5 2424.15
#Mann= 5 ,-1 , 0
       0     .06       0   81.67     .05       0   932.4    .045       0
   957.1     .05       0 1844.63      .1       0
Bank Sta=932.4,957.1
XS Rating Curve= 0 ,0
Exp/Cntr(USF)=0,0
Exp/Cntr=0.3,0.1

Type RM Length L Ch R = 1 ,7106    ,441.9,517.9,499
XS GIS Cut Line= 3
2069471.25580577329224.6513258292069932.96504313329252.777344636
2071489.29736632330236.026140757
#Sta/Elev= 30
       0 2472.81      45 2459.65    53.7  2456.4    72.1  2451.8    80.1 2448.04
  107.212428.676   115.6 2422.81   123.3 2420.65   166.5 2418.73   188.2 2413.16
   199.9 2411.82   246.5 2410.35  398.442410.222  421.392410.298   765.3 2410.12
   793.9  2410.4   862.1 2409.79  1028.6 2410.47  1036.3 2409.76  1071.2 2410.47
  1737.3 2412.27  1899.9 2413.81  1911.6 2413.09  1919.3 2413.92  2012.2 2416.23
  2105.2 2416.94    2115 2416.13  2159.4 2417.87 2256.372418.506  2303.9  2417.5
#Mann= 7 ,-1 , 0
       0     .06       0  107.21     .05       0  398.44     .07       0
  421.39     .05       0   765.3    .045       0   793.9     .05       0
 2256.37      .1       0
Bank Sta=765.3,793.9
XS Rating Curve= 0 ,0
Exp/Cntr(USF)=0,0
Exp/Cntr=0.3,0.1

Type RM Length L Ch R = 1 ,6588    ,247.7,256.7,261.3
XS GIS Cut Line= 2
2069509.06692696329304.9870081722071352.24084426330732.265272337
#Sta/Elev= 30
       0 2418.65    38.4 2417.42    79.9 2413.95   133.8 2411.99  312.462410.263
  350.842410.416  476.832409.979   566.2 2409.55   587.6 2408.77   598.5 2409.56
   701.4 2410.02   731.8 2409.11   814.3 2410.12   847.5 2409.11 1438.952412.131
 1479.082412.248  1627.6 2413.88  1640.1 2412.55  1648.5 2413.75 1785.572414.053
    2026 2415.41    2109 2417.16  2129.7 2415.25  2142.2 2417.86  2167.1 2416.86
  2211.2 2417.46    2222 2415.34  2230.8 2417.22  2320.6 2417.96  2331.2 2415.85
#Mann= 9 ,-1 , 0
       0     .06       0  312.46      .1       0  350.84     .07       0
  476.83      .1       0   566.2    .045       0   598.5      .1       0
 1438.95      .1       0 1479.08      .1       0 1785.57      .1       0
Bank Sta=566.2,598.5
XS Rating Curve= 0 ,0
Exp/Cntr(USF)=0,0
Exp/Cntr=0.3,0.1