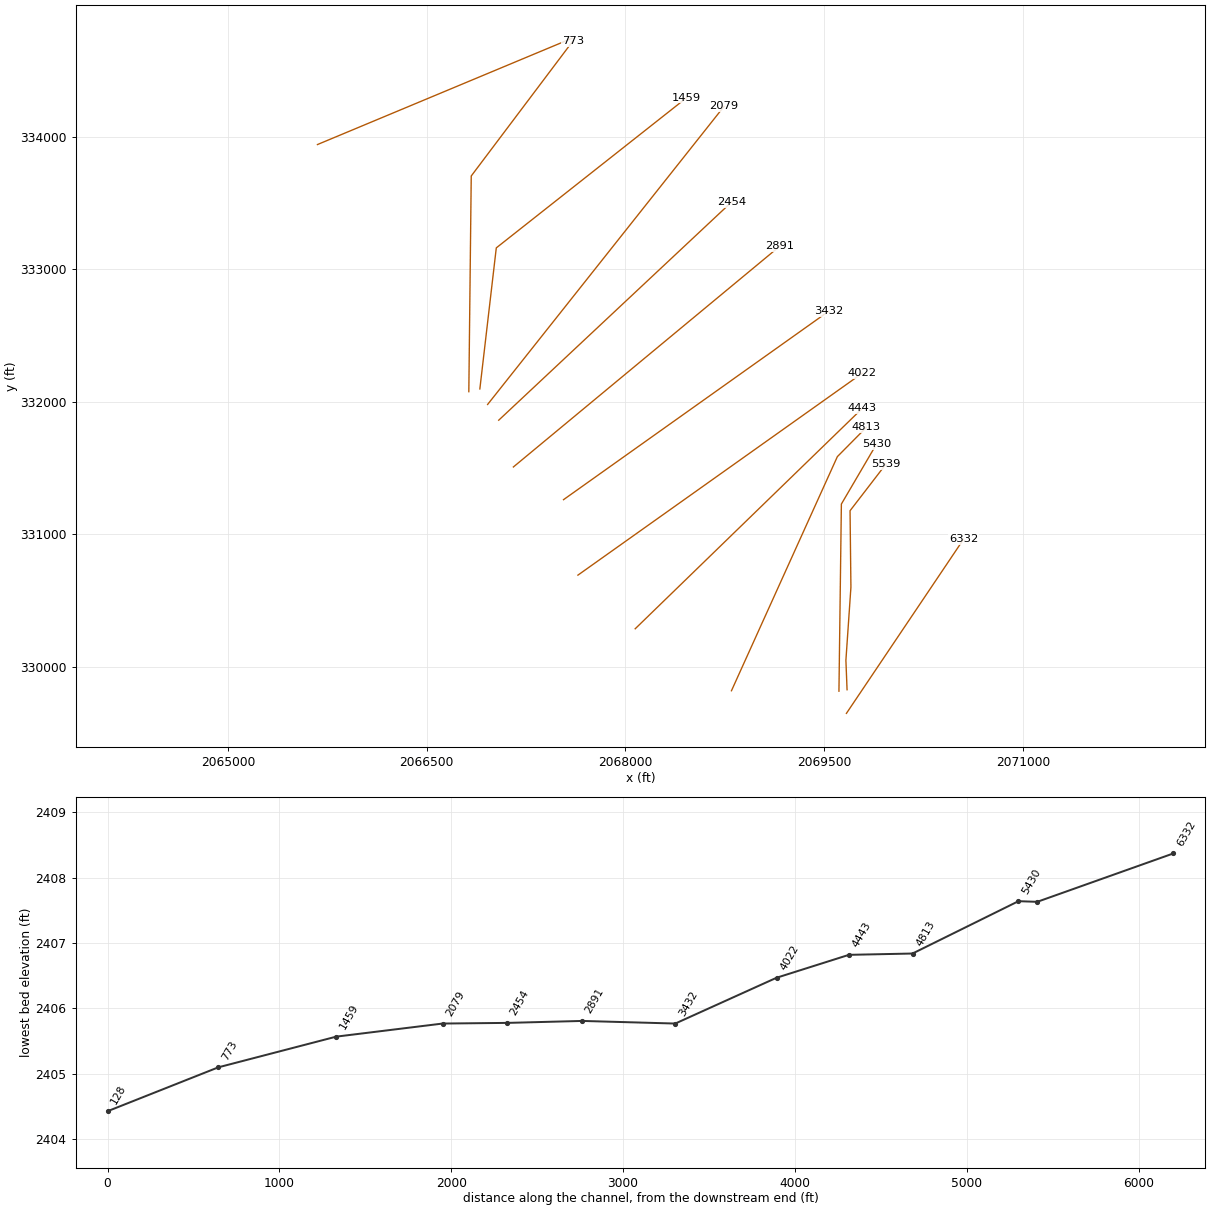
HEC-RAS study OTTERCK.prj: OTTERCK

--- OTTERCK.g01 (geometry) --- (continued)

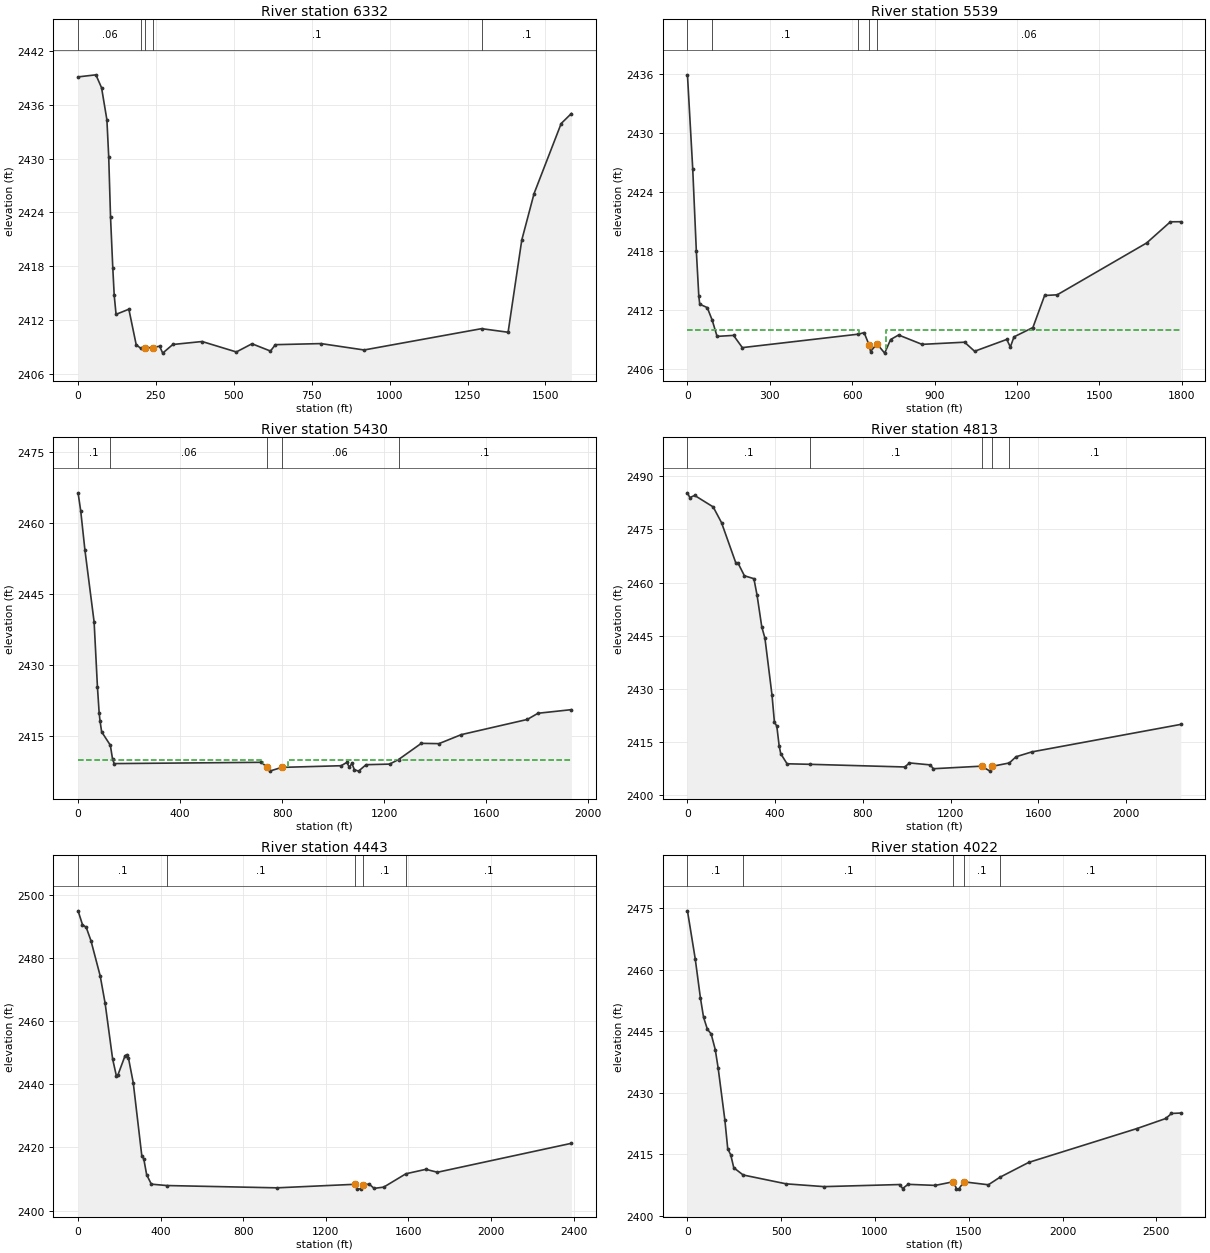
Type RM Length L Ch R = 1 ,6332    ,823.7,792.7,838.9
XS GIS Cut Line= 2
2069668.26044037329647.7501413312070552.03870328330961.602318277
#Sta/Elev= 30
       0 2439.07    57.2  2439.3    75.4 2437.86    92.5  2434.3    98.3 2430.21
   104.2 2423.46   111.4 2417.84     116 2414.79   121.9 2412.68     163 2413.25
   186.5 2409.31  201.252408.899   214.9 2408.98   239.4 2408.98   261.7 2409.14
   271.6 2408.37   304.1 2409.33   398.1 2409.66     508  2408.5   558.2 2409.41
   617.5  2408.6   633.3 2409.31   779.6 2409.43     918 2408.72  1295.2 2411.09
  1380.3 2410.69  1424.2 2420.94  1463.7 2426.11  1550.7 2433.89  1583.4    2435
#Mann= 5 ,-1 , 0
       0     .06       0  201.25      .1       0   214.9    .045       0
   239.4      .1       0  1295.2      .1       0
Bank Sta=214.9,239.4
XS Rating Curve= 0 ,0
Exp/Cntr(USF)=0,0
Exp/Cntr=0.5,0.3

Type RM Length L Ch R = 1 ,5539    ,83.7,109.1,89.3
XS GIS Cut Line= 5
2069673.15079971329826.0133691442069664.36610029330048.470510662
2069702.26744682330600.5118622432069695.67590829331177.271483298
2069965.92898787331528.270909826
#Sta/Elev= 30
       0 2435.88    19.2 2426.33    32.3 2418.01    41.3 2413.43    44.7  2412.6
    72.1 2412.25   90.17 2410.97   107.8 2409.33   167.8 2409.43   199.8 2408.19
  622.042409.555   643.2 2409.71   660.9 2408.48   666.7 2407.79   689.7 2408.58
   717.9 2407.63   739.5 2409.01   768.7 2409.47     854 2408.52  1008.8 2408.74
  1045.3 2407.82  1162.4 2409.02  1175.5 2408.25  1188.7 2409.28  1257.6 2410.23
  1300.2 2413.48  1346.1 2413.55  1671.5 2418.81  1758.1 2420.96  1795.8 2420.97
#Mann= 5 ,-1 , 0
       0     .06       0   90.17      .1       0  622.04     .06       0
   660.9    .045       0   689.7     .06       0
#XS Ineff= 2 , 0
          624.21    2410   723.1            2410
Permanent Ineff=
       F       F
Bank Sta=660.9,689.7
XS Rating Curve= 0 ,0
Exp/Cntr(USF)=0,0
Exp/Cntr=0.5,0.3

Type RM Length L Ch R = 1 ,5430    ,618.9,616.6,595.6
XS GIS Cut Line= 3
 2069611.8717361329815.1084650052069630.22179868331227.632071255
2069893.90435476331677.633919879
#Sta/Elev= 30
       0 2466.36    10.4 2462.53    26.8  2454.3    62.9  2439.1      76 2425.31
    82.6 2419.96    85.9  2418.3    92.4 2415.93  126.432413.112   135.1  2410.2
   141.6 2409.23   719.1  2409.5  740.82 2408.44   752.1 2407.66   798.7 2408.43
  1031.4 2408.78  1053.8 2409.48  1063.6 2408.46  1073.5 2409.27  1083.3 2407.95
  1099.7 2407.64  1129.3    2409  1221.4 2409.12 1256.452410.082  1345.8  2413.5
    1415 2413.44  1502.5 2415.34  1761.1 2418.54  1803.4 2419.85  1934.2 2420.61
#Mann= 5 ,-1 , 0
       0      .1       0  126.43     .06       0  740.82    .045       0
   798.7     .06       0 1256.45      .1       0
#XS Ineff= 2 , 0
           726.2    2410  821.56            2410
Permanent Ineff=
       F       F
Bank Sta=740.82,798.7
XS Rating Curve= 0 ,0
Exp/Cntr(USF)=0,0
Exp/Cntr=0.5,0.3

Type RM Length L Ch R = 1 ,4813    ,370.7,370,354.5
XS GIS Cut Line= 3
2068800.63209466329818.5613778292069599.91595695331585.498786263
2069818.00454832331805.654568076
#Sta/Elev= 30
       0 2485.28    10.7 2483.95      33 2484.54   117.3 2481.31   155.3 2476.88
   220.1  2465.6   230.9 2465.43   259.7  2461.9   302.9 2461.08   317.3 2456.46
   338.9 2447.48   353.3  2444.3   385.7 2428.18   396.5 2420.65   407.4 2419.52
   418.1 2413.97   425.3 2411.76   454.1 2408.91  558.682408.762   990.7 2408.01
  1012.4 2409.15  1106.5  2408.6  1121.4 2407.52  1340.9 2408.24  1379.6 2406.84
  1390.4  2408.2 1467.862409.147    1498 2410.89  1570.2 2412.26  2249.2 2420.01
#Mann= 5 ,-1 , 0
       0      .1       0  558.68      .1       0  1340.9    .045       0
  1390.4      .1       0 1467.86      .1       0
Bank Sta=1340.9,1390.4
XS Rating Curve= 0 ,0
Exp/Cntr(USF)=0,0
Exp/Cntr=0.3,0.1

Type RM Length L Ch R = 1 ,4443    ,416.9,421.3,413.1
XS GIS Cut Line= 2
2068074.13166152 330286.368281542069789.03296201331950.700451475
#Sta/Elev= 30
       0 2494.85    21.3 2490.47    39.4 2489.63    62.3 2485.42   107.1 2474.27
   130.9 2465.65   167.4 2447.98   185.7 2442.58   192.9 2442.92   227.7 2449.03
     238 2449.39     244 2448.32   267.2  2440.5   308.7 2417.37   318.2  2416.4
   332.2 2411.37   354.9 2408.39  430.132407.955   963.5 2407.23  1341.4 2408.35
    1353 2406.82  1371.6 2406.92    1379 2408.24    1411 2408.38  1433.8 2407.06
  1480.6 2407.45 1588.122411.678  1684.8 2413.08  1740.8 2412.16  2389.7 2421.31
#Mann= 5 ,-1 , 0
       0      .1       0  430.13      .1       0  1341.4    .045       0
    1379      .1       0 1588.12      .1       0
Bank Sta=1341.4,1379
XS Rating Curve= 0 ,0
Exp/Cntr(USF)=0,0
Exp/Cntr=0.3,0.1

Type RM Length L Ch R = 1 ,4022    ,572.6,589.5,579.5
XS GIS Cut Line= 2
2067641.81937289330691.1651195852069786.41261456332214.015364647
#Sta/Elev= 30
       0 2474.34    41.3 2462.68    68.8  2453.2    85.8 2448.39   106.2 2445.47
   126.3 2444.32   148.2 2440.51   163.6 2436.03   199.2 2423.44   214.8 2416.31
   230.9 2414.81     247 2411.68  296.962409.921     526 2407.76   728.3 2407.08
  1132.3 2407.59  1147.2 2406.62  1176.5 2407.64  1321.2 2407.38    1418 2408.27
  1434.5 2406.58  1446.1 2406.47  1474.2 2408.25  1604.5 2407.53 1665.982409.361
  1819.8 2412.99  2395.8 2421.23  2550.8  2423.7  2580.9 2424.92  2630.3 2425.03
#Mann= 5 ,-1 , 0
       0      .1       0  296.96      .1       0    1418    .045       0
  1474.2      .1       0 1665.98      .1       0
Bank Sta=1418,1474.2
XS Rating Curve= 0 ,0
Exp/Cntr(USF)=0,0
Exp/Cntr=0.3,0.1

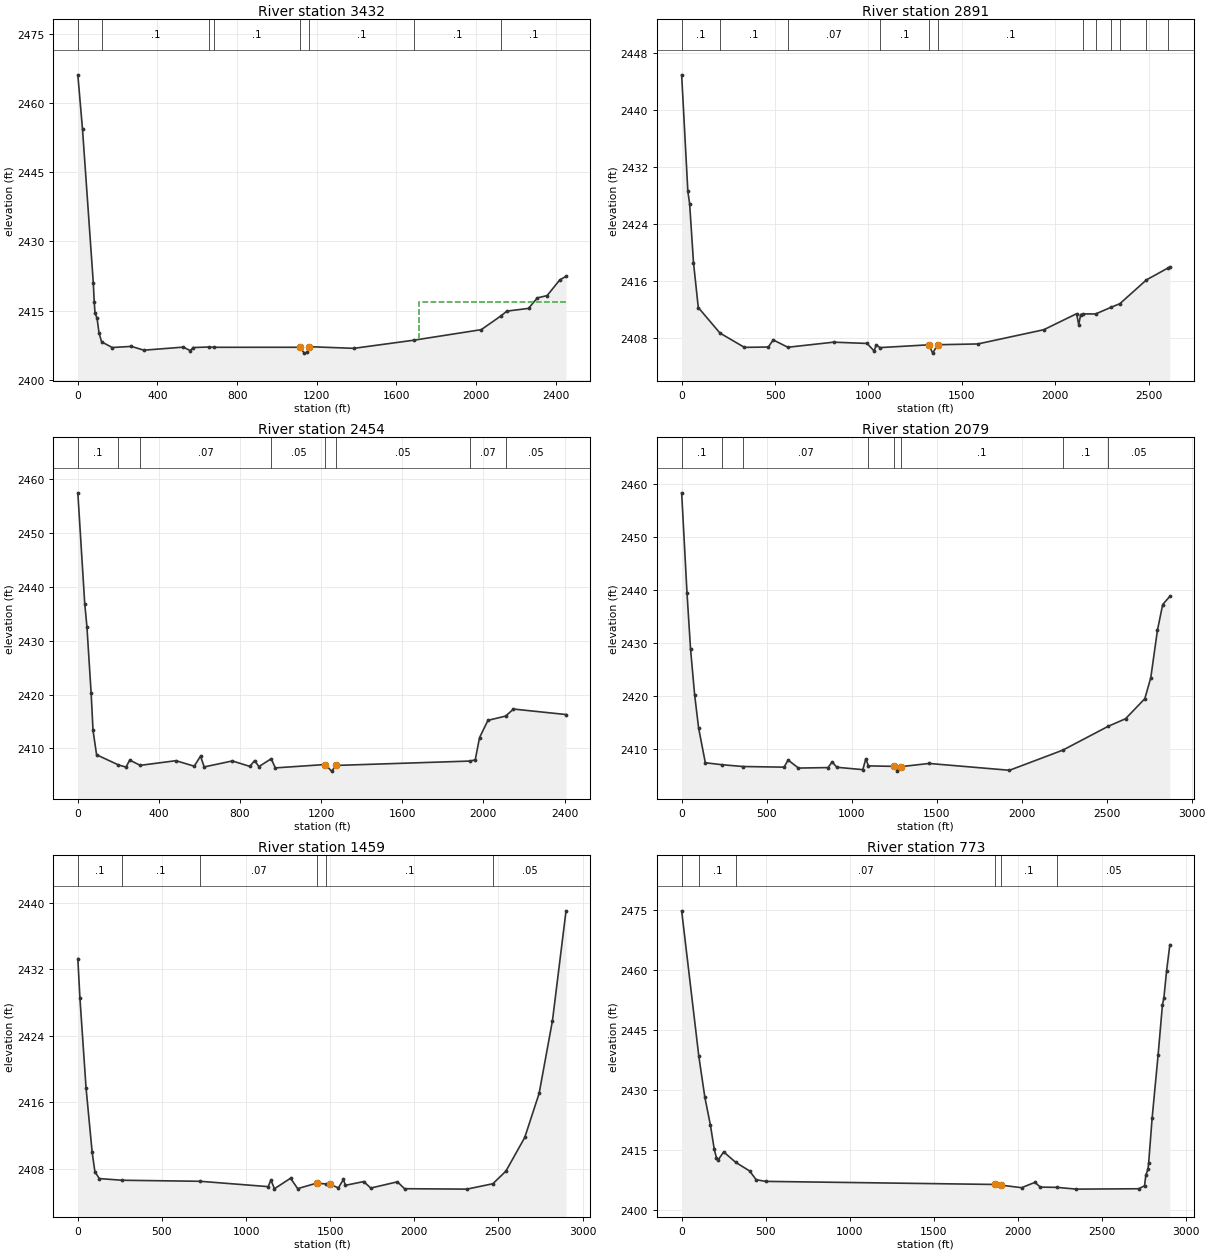
Type RM Length L Ch R = 1 ,3432    ,533.1,541.1,540
XS GIS Cut Line= 2
2067533.22391453331260.7930493512069532.35870175332681.454791762
#Sta/Elev= 30
       0 2466.16    23.6 2454.32    77.7 2421.03    82.5 2416.81    86.5 2414.41
    96.5 2413.39   106.6 2410.13   119.62408.209   172.9 2406.99   269.2 2407.23
   331.8 2406.41   529.7 2407.07   565.5 2406.31   578.8 2406.98  658.852407.101
  685.132407.034  1116.9 2407.04    1137 2405.77  1152.7 2405.96  1161.1 2407.17
  1386.5 2406.81 1687.152408.572  2026.5 2410.86 2126.622413.879  2155.2 2414.88
    2264 2415.48  2308.2 2417.75  2357.6 2418.26  2420.9 2421.65  2452.5 2422.43
#Mann= 8 ,-1 , 0
       0      .1       0   119.6      .1       0  658.85     .07       0
  685.13      .1       0  1116.9    .045       0  1161.1      .1       0
 1687.15      .1       0 2126.62      .1       0
#XS Ineff= 2 , 0
                         1713.81         2416.87
Permanent Ineff=
       F       F
Bank Sta=1116.9,1161.1
XS Rating Curve= 0 ,0
Exp/Cntr(USF)=0,0
Exp/Cntr=0.3,0.1

Type RM Length L Ch R = 1 ,2891    ,430,436.9,441.9
XS GIS Cut Line= 2
2067154.66434844331507.4947890512069166.55957047333174.858271162
#Sta/Elev= 30
       0 2444.92    33.1 2428.56    42.8 2426.79    63.4 2418.53      89 2412.22
   205.22408.625   335.9 2406.62   464.2 2406.67   489.8 2407.67  568.312406.636
   813.3 2407.35   992.3 2407.17  1030.4 2406.11  1040.3 2406.91 1063.79 2406.59
  1323.1 2406.98  1343.6 2405.81  1370.5 2406.99  1585.3  2407.1  1938.3  2409.1
  2113.8 2411.35  2125.5 2409.79  2135.4 2411.23 2147.882411.329 2215.242411.312
 2298.872412.256 2345.412412.756 2487.872416.107 2600.882417.744    2613 2417.91
#Mann= 12 ,-1 , 0
       0      .1       0   205.2      .1       0  568.31     .07       0
 1063.79      .1       0  1323.1    .045       0  1370.5      .1       0
 2147.88      .1       0 2215.24     .05       0 2298.87     .07       0
 2345.41     .05       0 2487.87     .07       0 2600.88     .05       0
Bank Sta=1323.1,1370.5
XS Rating Curve= 0 ,0
Exp/Cntr(USF)=0,0
Exp/Cntr=0.3,0.1

Type RM Length L Ch R = 1 ,2454    ,368.3,375.8,367.7
XS GIS Cut Line= 2
 2067044.0739134331860.5334855182068800.76043919333506.629576275
#Sta/Elev= 30
       0 2457.47    34.1  2436.9    44.8 2432.64    65.6  2420.3      75 2413.34
    92.5 2408.82  199.872406.938   237.5 2406.53     256 2407.83  307.742406.853
   483.7 2407.72     574  2406.7   605.1 2408.57   623.1 2406.56     762 2407.67
   847.9 2406.66   871.9 2407.74   892.9 2406.62  953.762408.079   973.8 2406.38
  1221.1 2407.01    1251 2405.78    1275 2406.84 1934.512407.651  1959.7 2407.88
  1980.9    2412  2022.4 2415.21 2109.512416.004  2148.3 2417.31  2407.4 2416.29
#Mann= 8 ,-1 , 0
       0      .1       0  199.87     .05       0  307.74     .07       0
  953.76     .05       0  1221.1    .045       0    1275     .05       0
 1934.51     .07       0 2109.51     .05       0
Bank Sta=1221.1,1275
XS Rating Curve= 0 ,0
Exp/Cntr(USF)=0,0
Exp/Cntr=0.3,0.1

Type RM Length L Ch R = 1 ,2079    ,622.1,619.2,610.8
XS GIS Cut Line= 2
2066960.19272685 331979.376015062068744.86713967334229.168276776
#Sta/Elev= 30
       0 2458.37    31.4 2439.48    52.3 2428.86    76.2 2420.25    99.6 2413.95
   139.3 2407.35  239.482406.974   360.12406.643   602.6 2406.52   626.1 2407.87
   687.1 2406.35   860.9 2406.44   885.7 2407.52   912.3  2406.5  1065.8 2406.05
    1083 2408.08 1098.962406.762    1250 2406.67  1267.8 2405.77  1288.9 2406.61
  1455.2 2407.22  1928.4 2405.93  2241.82409.733 2508.992414.241    2611 2415.67
  2724.4 2419.46  2759.5 2423.42  2798.7 2432.39  2829.5 2437.26  2871.7  2438.8
#Mann= 8 ,-1 , 0
       0      .1       0  239.48      .1       0   360.1     .07       0
 1098.96      .1       0    1250    .045       0  1288.9      .1       0
  2241.8      .1       0 2508.99     .05       0
Bank Sta=1250,1288.9
XS Rating Curve= 0 ,0
Exp/Cntr(USF)=0,0
Exp/Cntr=0.3,0.1

Type RM Length L Ch R = 1 ,1459    ,659.2,686.3,662.6
XS GIS Cut Line= 3
2066901.62233107332096.5168066352067025.65375744333161.119883006
2068462.35111293334294.629307362
#Sta/Elev= 30
       0 2433.31    12.5 2428.57    48.9 2417.75    85.2    2410   101.7 2407.64
   128.1 2406.84  262.942406.639  728.092406.513  1131.1 2405.87  1147.9 2406.66
  1168.7 2405.62  1264.5 2406.88  1306.7 2405.63  1419.5 2406.29    1476 2406.19
  1497.1 2406.16    1549 2405.72  1578.3 2406.73  1590.8 2406.03  1699.5 2406.48
  1741.1  2405.7  1899.7 2406.45  1941.9 2405.62  2312.9 2405.57 2467.05 2406.22
  2544.6 2407.74  2656.5 2411.79  2741.9 2417.09  2821.3 2425.86  2901.8 2439.06
#Mann= 6 ,-1 , 0
       0      .1       0  262.94      .1       0  728.09     .07       0
  1419.5    .045       0    1476      .1       0 2467.05     .05       0
Bank Sta=1419.5,1497.1
XS Rating Curve= 0 ,0
Exp/Cntr(USF)=0,0
Exp/Cntr=0.3,0.1

Type RM Length L Ch R = 1 ,773     ,643.2,644.8,605.1
XS GIS Cut Line= 3
2066818.33450044332075.7088959592066836.60737321333703.835201403
2067604.20266197334722.816172641
#Sta/Elev= 30
       02474.741 102.1582438.336 137.9782428.089  171.062421.125 194.0272415.063
 207.151 2412.91 216.9942412.389 249.805 2414.42 321.9882411.792 404.0142409.655
 443.3862407.457 499.1642407.0411864.1482406.2681898.8422406.1072022.0682405.456
2101.6342406.8042133.5642405.603 2231.962405.5442347.0082405.1012717.7952405.195
 2753.212405.921 2761.452408.6312773.7482410.0732777.8212411.5862798.393 2422.79
2834.0472438.6282860.0062451.2632868.2212452.8692884.652 2459.752903.9742466.262
#Mann= 6 ,-1 , 0
       0      .1       0 102.158      .1       0 321.988     .07       0
1864.148    .045       01898.842      .1       0 2231.96     .05       0
Bank Sta=1864.148,1898.842
XS Rating Curve= 0 ,0
Exp/Cntr(USF)=0,0
Exp/Cntr=0.3,0.1

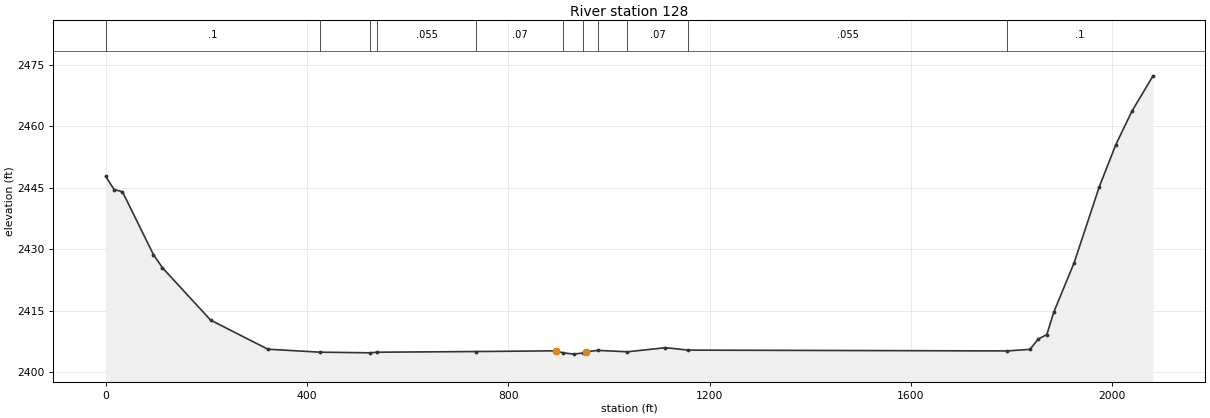
Type RM Length L Ch R = 1 ,128     ,129,129,129
XS GIS Cut Line= 2
2065675.81663902333940.9472396562067596.21043288334742.672064732
#Sta/Elev= 30
       0  2447.8    16.5 2444.61    33.2 2444.07    94.7 2428.73   112.5 2425.53
   208.4 2412.73   322.2 2405.63   425.3 2404.91   524.7 2404.75   539.9  2404.9
   735.5 2405.06   894.6 2405.24  908.77 2404.74   930.2 2404.43   947.9 2404.71
     955 2405.03   978.8 2405.34  1036.8    2405  1112.3    2406  1157.7 2405.41
  1791.4 2405.21  1836.8  2405.6  1853.2  2408.1  1870.2 2409.21  1884.2 2414.74
  1924.4 2426.71  1974.5  2445.3  2007.4 2455.59  2039.4 2463.76  2081.3 2472.37
#Mann= 11 ,-1 , 0
       0      .1       0   425.3    .055       0   524.7     .07       0
   539.9    .055       0   735.5     .07       0  908.77    .045       0
   947.9     .05       0   978.8    .055       0  1036.8     .07       0
  1157.7    .055       0  1791.4      .1       0
Bank Sta=894.6,955
XS Rating Curve= 0 ,0
Exp/Cntr(USF)=0,0
Exp/Cntr=0.3,0.1
LCMann Table=0

Chan Stop Cuts=-1
Use User Specified Reach Order=0
Composite Channel Slope=5